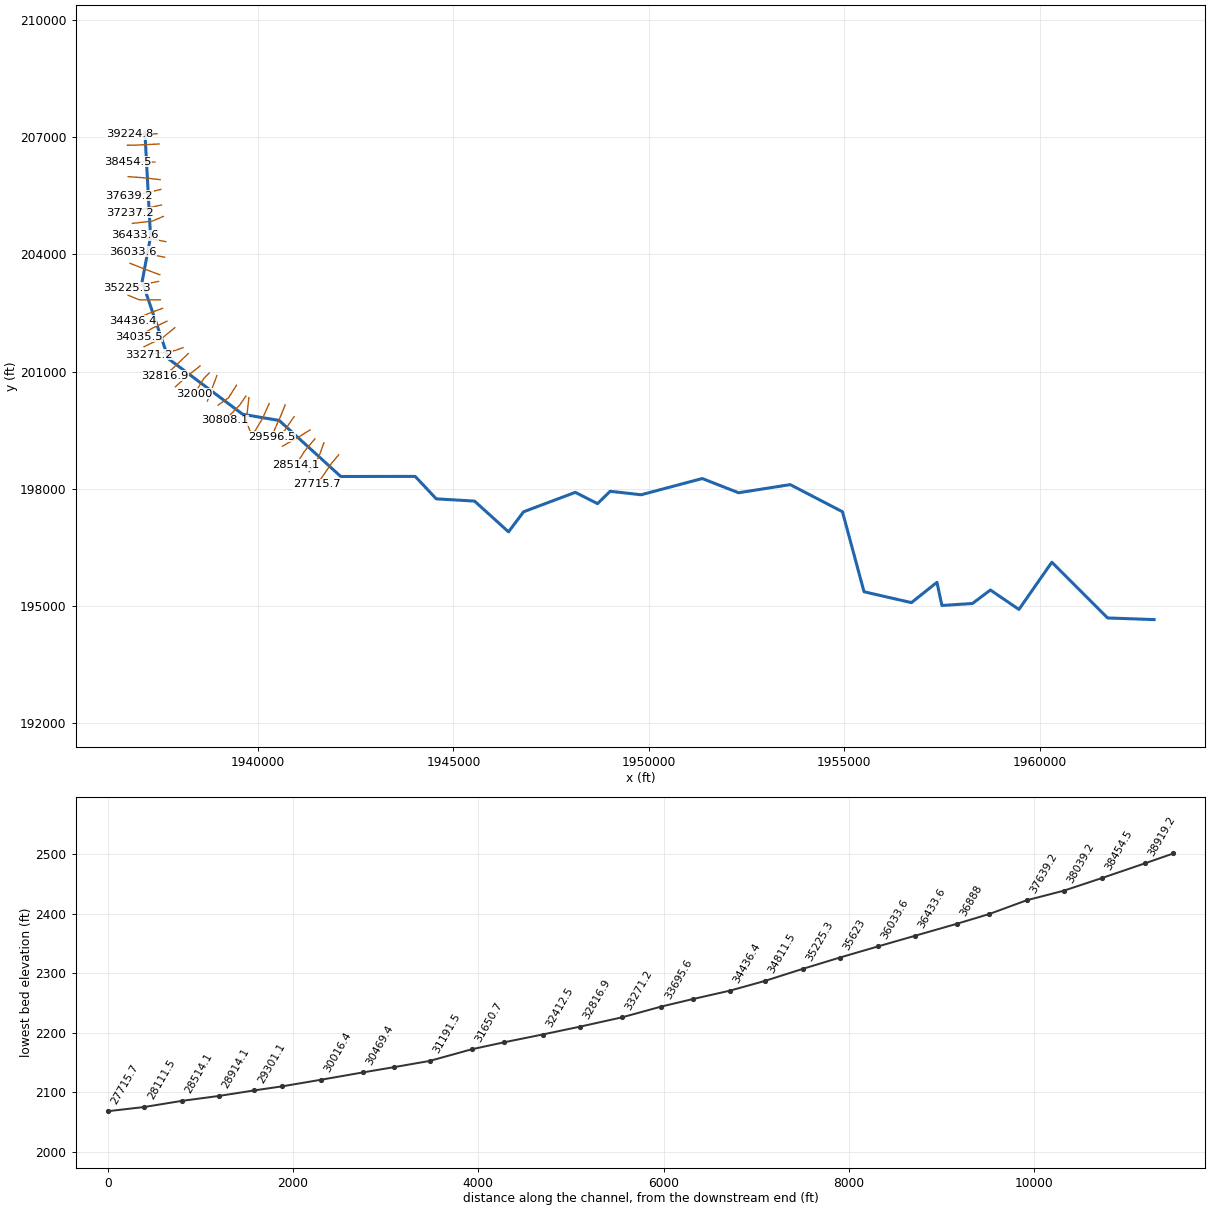
--- MntnCrk.prj (project) ---

Proj Title=MntnCrk
Current Plan=p01
Default Exp/Contr=0,0
English Units
Geom File=g01
Flow File=f01
Plan File=p01
BEGIN DESCRIPTION:
END DESCRIPTION:
DSS Export Rating Curves= 0
DSS Export Rating Curve Sorted= 0
DSS Export Volume Flow Curves= 0
DXF OffsetX= 0
DXF OffsetY= 0
DXF ScaleX= 0
DXF ScaleY= 0

--- MntnCrk.p01 (plan) ---

Plan Title=Floodplain
Program Version=4.00
Geom File=g01
Flow File=f01
K Sum by GR=0
Std Step Tol=0.01
Critical Tol=0.01
Num of Std Step Trials=20
Max Error Tol=0.3
Flow Tol Ratio=0.001
Split Flow NTrial=30
Split Flow Tol=0.02
Split Flow Ratio=0.02
Log Output Level=0
Friction Slope Method=1
Unsteady Friction Slope Method=2
Unsteady Bridges Friction Slope Method=1
Global Log Level=0
CheckData=False
Run HTab=0
Run UNet=0
Run PostProcess=0
UNET Theta=0
UNET Theta Warmup=0
UNET ZTol=0
UNET ZSATol=0
UNET MxIter=0
UNET MaxInSteps=0
UNET DtIC=0
UNET DtMin=0
UNET MaxCRTS=0
UNET WFStab=0
UNET SFStab=0
UNET WFX=0
UNET SFX=0
UNET DSS MLevel=0
UNET DZMax Abort=0
UNET Convert EG Bridges=0
UNET Use Existing IB Tables=0
UNET Froude Limit=0
UNET Froude Power=0
Write IC File=0
Echo Input=False
Echo Output=False
Write Detailed=0

--- MntnCrk.f01 (steady flow) ---

Flow Title=NFF Regression Equation
Program Version=4.00
Number of Profiles=1
Profile Names=P100yr
River Rch & RM=MntnCrk,Main      ,39224.8
304.1069
River Rch & RM=MntnCrk,Main      ,38919.2
517.1070
River Rch & RM=MntnCrk,Main      ,36433.6
572.2386
River Rch & RM=MntnCrk,Main      ,35225.3
633.9459
River Rch & RM=MntnCrk,Main      ,30808.1
701.8601
River Rch & RM=MntnCrk,Main      ,30469.4
792.4283
River Rch & RM=MntnCrk,Main      ,29301.1
856.8538
River Rch & RM=MntnCrk,Main      ,27296.8
903.9352
River Rch & RM=MntnCrk,Main      ,26895.4
1166.639
River Rch & RM=MntnCrk,Main      ,25695.3
1210.317
River Rch & RM=MntnCrk,Main      ,20890
1340.717
River Rch & RM=MntnCrk,Main      ,20513
1769.767
River Rch & RM=MntnCrk,Main      ,14151.6
1878.439
River Rch & RM=MntnCrk,Main      ,13743.3
2988.318
River Rch & RM=MntnCrk,Main      ,6908.4
3227.440
River Rch & RM=MntnCrk,Main      ,506.9
3580.010
Boundary for River Rch & Prof#=MntnCrk,Main      ,1
Up Type=0
Dn Type=3
Dn Slope=0.028909

--- MntnCrk.g01 (geometry) ---

Geom Title=USGS 3m DEM
Program Version=4.10

River Reach=MntnCrk         ,Main
Reach XY= 30
     1937107.518      207125.473     1937252.217      204446.682
     1937037.033      203302.255     1937711.501      201325.527
     1939610.437      199905.536     1940543.957      199747.974
     1942117.975      198314.889      1944023.77      198316.645
     1944562.246      197742.481     1945541.009      197685.186
     1946411.404      196898.057     1946796.345      197411.571
     1948119.669      197908.965     1948688.223      197620.134
     1949010.881      197936.287     1949802.532      197846.622
     1951367.334      198262.232     1952296.731       197898.38
     1953618.157      198106.719     1954954.598       197412.97
     1955507.154      195365.013      1956719.43       195087.48
     1957372.732      195606.487     1957499.274      195014.645
     1958280.027      195064.435     1958739.691      195409.885
      1959470.43      194913.624     1960311.907      196120.848
     1961737.285      194695.181     1962927.714      194653.317

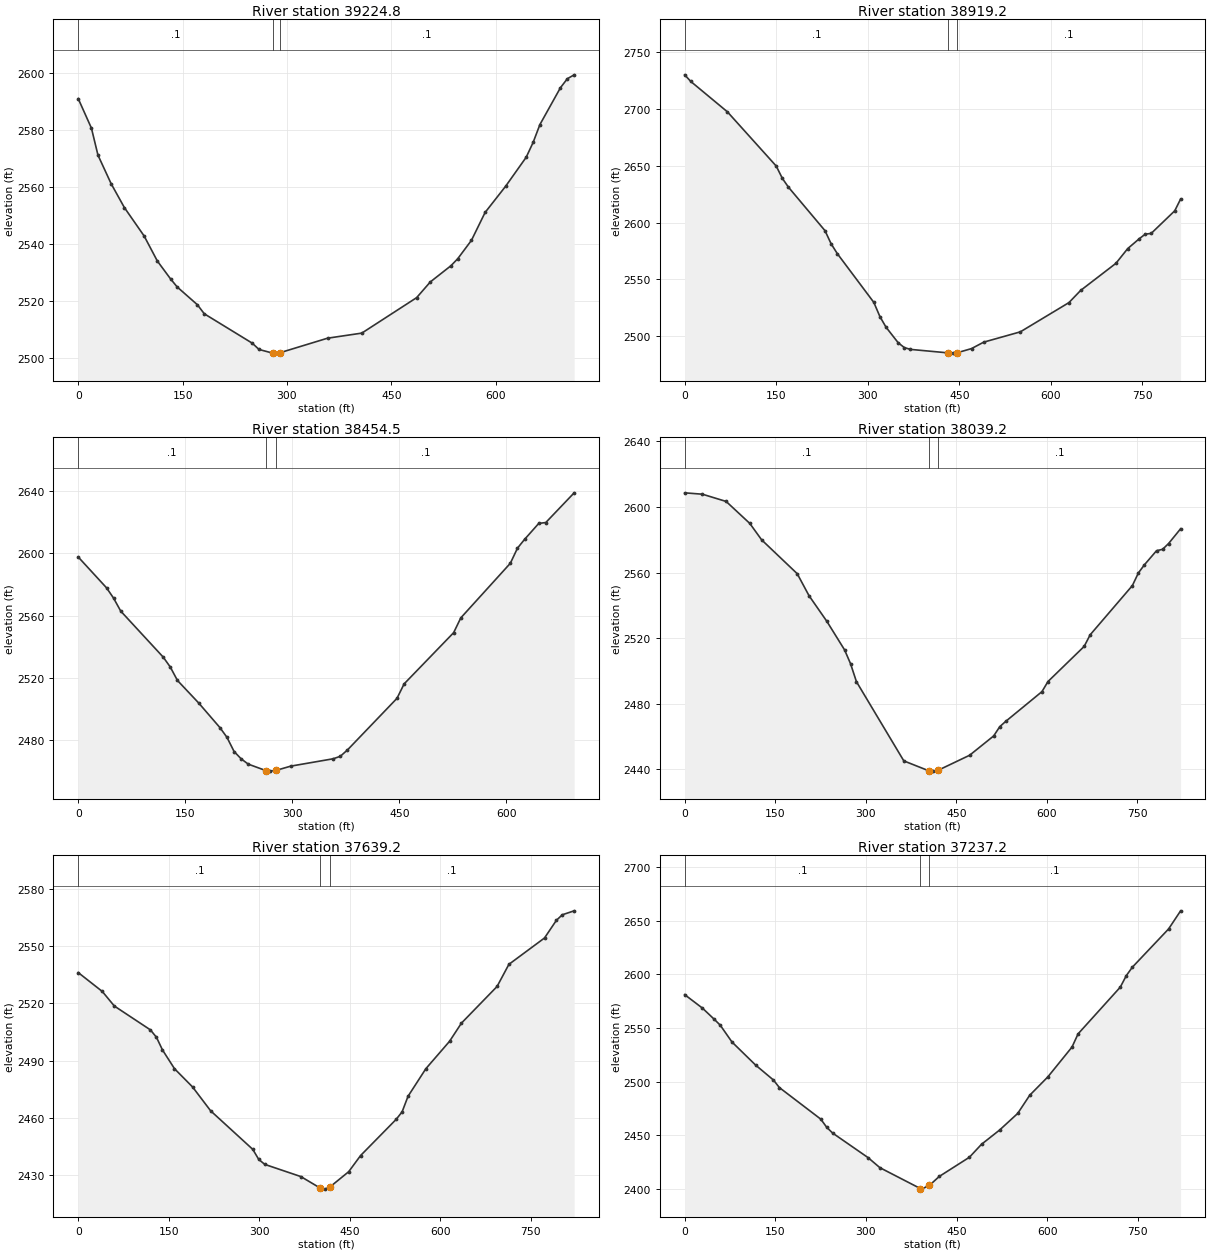
Type RM Length L Ch R = 1 ,39224.8 ,304.1,305.3,306.6
XS GIS Cut Line= 3
     1937418.872      207084.945     1937267.294      207080.735
     1936706.245      207068.103
#Sta/Elev= 30
       0 2591.01      19 2580.66    28.4 2571.18    47.4 2561.13    66.3 2552.82
    94.8 2542.81   113.7 2534.06   132.7 2527.79   142.2 2524.96   171.3 2518.71
   181.2 2515.54   250.1 2505.24   259.9 2503.02   279.6 2501.74   289.5 2501.85
   358.4 2506.98   407.6 2508.76   486.4  2521.2   506.1 2526.72   535.6 2532.37
   545.4 2534.83   565.2 2541.31   584.8 2551.08   614.4  2560.3   643.9 2570.46
   653.8 2575.63   663.6 2581.92   693.1 2594.84     703 2597.99   712.8 2599.36
#Mann= 3 , 0 , 0
       0      .1       0   279.6    .045       0   289.5      .1       0
Bank Sta=279.6,289.5
XS Rating Curve= 0 ,0
Exp/Cntr=0.3,0.1

Type RM Length L Ch R = 1 ,38919.2 ,465.8,464.8,463.8
XS GIS Cut Line= 3
     1937471.447      206822.256      1936852.37      206791.376
     1936659.739      206789.271
#Sta/Elev= 30
       0 2729.89      10 2724.07      70 2697.34     150 2649.65     160 2638.85
     170 2631.09   229.9 2592.83   239.9 2581.32   249.9 2572.75   309.9 2529.74
   319.9 2517.22   329.9 2507.93   349.9  2494.2   359.9 2489.99   369.9 2488.43
   431.7 2485.35   439.9 2485.14   446.7 2485.52   469.9 2489.12   489.9  2494.8
   549.9 2503.85   629.5 2529.56   648.7 2540.27   706.5 2564.11   725.8 2577.06
   745.1  2585.9   754.7 2589.79   764.3 2590.42   802.9 2610.32   812.5 2620.67
#Mann= 3 , 0 , 0
       0      .1       0   431.7    .045       0   446.7      .1       0
Bank Sta=431.7,446.7
XS Rating Curve= 0 ,0
Exp/Cntr=0.3,0.1

Type RM Length L Ch R = 1 ,38454.5 ,417.5,415,413.3
XS GIS Cut Line= 2
     1937365.408      206358.757     1936670.646      206363.036
#Sta/Elev= 30
       0 2597.55    39.7 2577.79    49.6 2571.15    59.6 2562.87   119.1  2533.4
     129 2527.06     139 2518.48   168.7 2504.07   198.5 2488.28   208.4 2482.03
   218.4 2472.93   228.3 2468.25   238.2 2464.86   262.7 2460.76     268 2460.38
   277.7 2460.92   297.8 2463.58   357.3  2468.3   367.2 2469.88   377.2 2473.94
   446.6 2507.02   456.6 2516.27     526 2549.09     536 2558.55   605.4 2593.52
   615.4 2603.21   625.3 2608.81   645.2 2619.05   655.1 2619.63   694.8 2638.65
#Mann= 3 , 0 , 0
       0      .1       0   262.7    .045       0   277.7      .1       0
Bank Sta=262.7,277.7
XS Rating Curve= 0 ,0
Exp/Cntr=0.3,0.1

Type RM Length L Ch R = 1 ,38039.2 ,392.2,400,405.6
XS GIS Cut Line= 3
     1937498.804      205908.785     1937089.505      205956.368
     1936681.161      205986.818
#Sta/Elev= 30
       0  2608.6    29.4 2607.76    68.7 2603.34   107.9 2589.93   127.5 2579.92
   186.4  2559.3     206 2545.86   235.5 2530.25   264.9 2512.81   274.7 2504.45
   284.5 2493.46     363 2445.15   404.6 2439.08   412.1 2438.91   419.6 2439.39
     472 2448.59   511.9 2460.39   521.9 2466.01   531.9 2469.28   591.8 2487.38
   601.8 2493.54   661.7 2514.95   671.7 2522.04   741.6 2552.05   751.6 2559.78
   761.6 2564.74   781.6  2573.3   791.6 2574.15   801.6  2577.7   821.5  2586.7
#Mann= 3 , 0 , 0
       0      .1       0   404.6    .045       0   419.6      .1       0
Bank Sta=404.6,419.6
XS Rating Curve= 0 ,0
Exp/Cntr=0.3,0.1

Type RM Length L Ch R = 1 ,37639.2 ,402.1,402,403.7
XS GIS Cut Line= 3
     1937512.223      205658.711     1937114.306      205564.964
     1936707.596       205494.07
#Sta/Elev= 30
       0 2536.13    39.9 2526.24    59.8 2518.63   119.6 2506.14   129.6 2502.28
   139.6 2495.65   159.5 2485.83   189.4 2476.29   219.4 2463.79   289.2 2443.62
   299.1 2438.36   309.1 2435.76   368.9 2429.38   401.3  2423.3   408.8 2422.82
   416.3 2423.78   448.1 2431.94   467.8 2440.39   526.8 2459.35   536.6 2463.26
   546.4  2471.4   575.9 2485.82   615.2 2500.17   634.9 2509.68   693.9 2528.85
   713.5 2540.43   772.5 2554.22   792.2 2563.47     802 2566.37   821.6 2568.43
#Mann= 3 , 0 , 0
       0      .1       0   401.3    .045       0   416.3      .1       0
Bank Sta=401.3,416.3
XS Rating Curve= 0 ,0
Exp/Cntr=0.3,0.1

Type RM Length L Ch R = 1 ,37237.2 ,352,349.3,345.6
XS GIS Cut Line= 3
     1937531.248      205261.417     1937129.894      205171.725
     1936735.249      205062.483
#Sta/Elev= 30
       0 2581.02    29.4 2568.44      49 2558.01    58.8 2552.58    78.3 2536.85
   117.5 2515.31   146.9 2501.43   156.7 2494.41   225.2    2465     235 2457.42
   244.8 2452.02   303.5 2429.11   323.1 2419.73   389.9 2400.34   391.7 2399.76
   404.9 2403.18   421.2 2411.54   471.2 2429.47   491.2 2441.54   521.1 2454.81
   551.1  2470.3     571 2487.25     601 2504.37     641 2532.19     651 2544.44
   720.9 2588.02   730.8 2598.71   740.8 2606.57   800.8 2642.24   820.7 2659.12
#Mann= 3 , 0 , 0
       0      .1       0   389.9    .045       0   404.9      .1       0
Bank Sta=389.9,404.9
XS Rating Curve= 0 ,0
Exp/Cntr=0.3,0.1

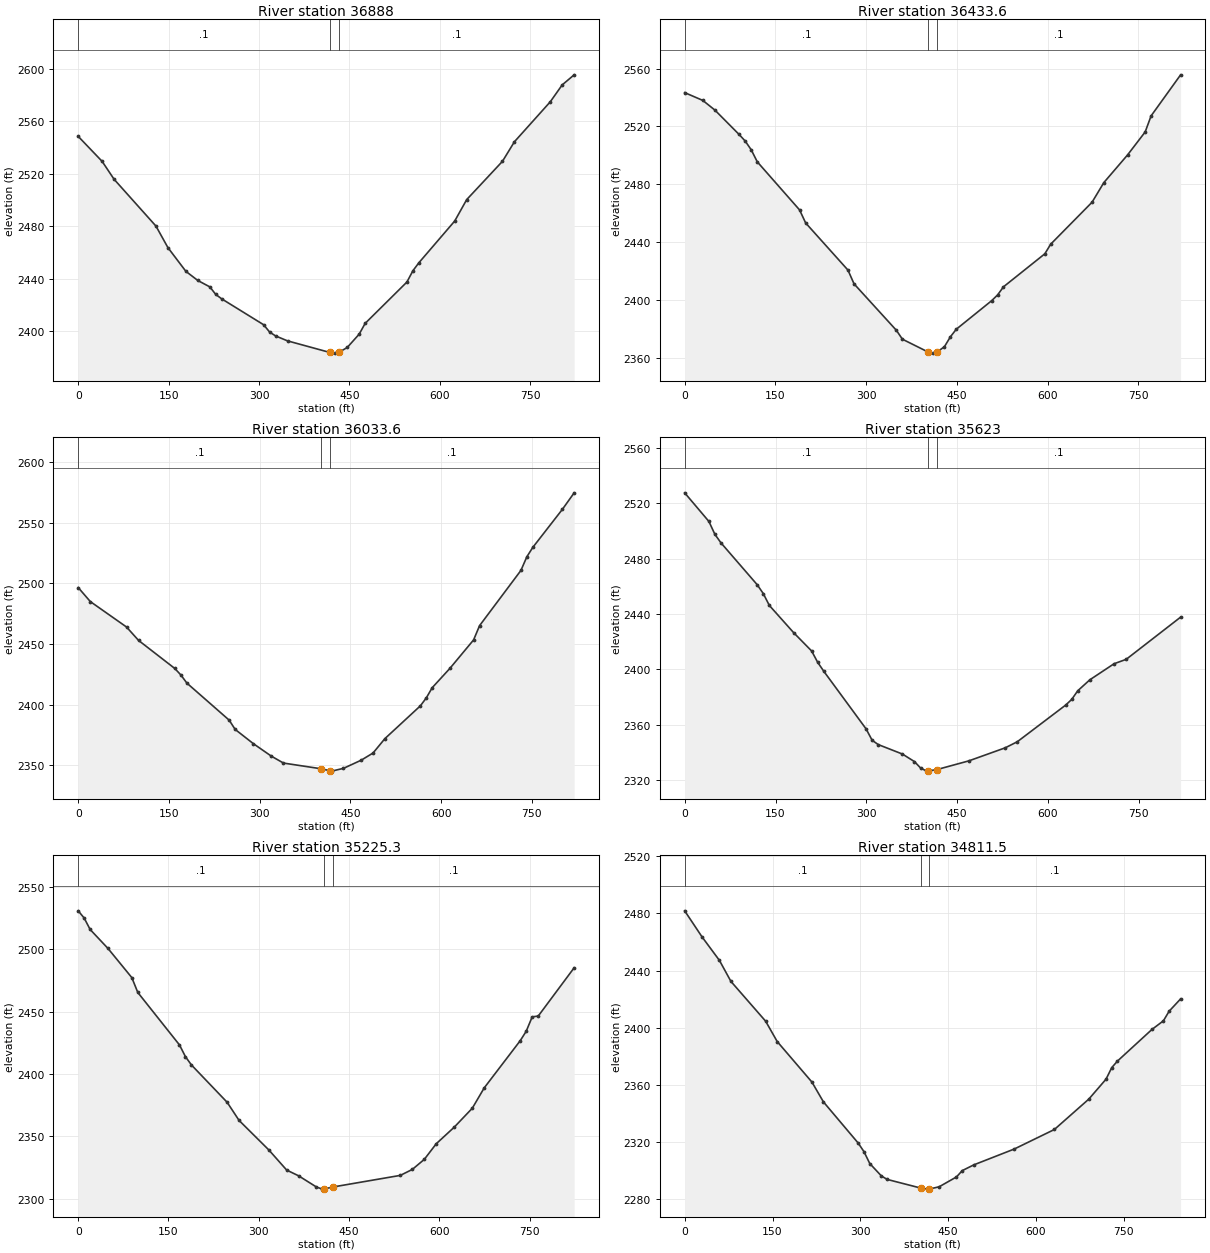
Type RM Length L Ch R = 1 ,36888   ,461.9,454.2,452.8
XS GIS Cut Line= 3
     1937579.974      204969.566     1937297.487      204847.934
     1936785.596      204789.953
#Sta/Elev= 30
       0 2548.47    39.7 2529.42    59.5  2515.8     129 2480.12   148.8 2463.74
   178.6 2445.67   198.4  2438.7   218.3 2433.83   228.2 2428.06   238.1 2424.69
   307.6 2404.98   317.5 2399.43   327.4 2396.46   347.2  2392.7   417.1 2383.91
   426.4 2383.36   432.1 2383.84   446.3 2387.68   466.1 2397.82     476 2406.02
   545.3 2437.53   555.2  2446.1   565.1 2452.18   624.6 2484.01   644.4 2500.28
   703.8 2529.49   723.6 2544.36   783.1 2574.82   802.9  2587.7   822.7 2595.36
#Mann= 3 , 0 , 0
       0      .1       0   417.1    .045       0   432.1      .1       0
Bank Sta=417.1,432.1
XS Rating Curve= 0 ,0
Exp/Cntr=0.3,0.1

Type RM Length L Ch R = 1 ,36433.6 ,400,399.9,401.8
XS GIS Cut Line= 3
     1937644.474      204323.862      1937241.44      204398.947
     1936841.522      204489.555
#Sta/Elev= 30
       0  2543.4      30 2537.99      50 2531.29      90 2514.42     100  2509.9
     110 2503.84     120 2495.51     190 2462.18     200 2453.19     270 2420.53
     280 2411.04     350 2378.88     360 2372.71   402.5 2363.84     410 2363.07
   417.5 2363.87   429.5 2367.54   439.3 2374.33     449 2379.58   507.6 2399.38
   517.4 2403.35   527.1 2408.96   595.5 2431.83   605.2 2438.49   673.6 2467.54
   693.1 2481.13   732.2 2500.22   761.4 2516.18   771.2  2527.3     820 2555.71
#Mann= 3 , 0 , 0
       0      .1       0   402.5    .045       0   417.5      .1       0
Bank Sta=402.5,417.5
XS Rating Curve= 0 ,0
Exp/Cntr=0.3,0.1

Type RM Length L Ch R = 1 ,36033.6 ,414.4,410.6,405.4
XS GIS Cut Line= 3
     1937612.388      203925.659     1937210.634      204003.776
     1936803.928      204061.333
#Sta/Elev= 30
       0 2496.57      20 2485.02    79.9 2464.02    99.8 2452.97   159.7 2429.82
   169.7 2424.48   179.7 2417.75   249.6  2387.2   259.5 2379.55   289.5 2367.83
   319.4 2357.47   339.4 2351.79   401.8 2347.07   416.8 2345.41   419.1 2345.14
   438.6 2347.44     468 2354.19   487.5 2360.09   507.1 2371.96   565.8 2399.03
   575.5 2405.53   585.3 2413.96   614.7 2429.98   653.8 2453.43   663.6 2465.14
     732 2510.72   741.8 2521.96   751.6  2529.7   800.5 2561.07     820 2574.72
#Mann= 3 , 0 , 0
       0      .1       0   401.8    .045       0   416.8      .1       0
Bank Sta=401.8,416.8
XS Rating Curve= 0 ,0
Exp/Cntr=0.3,0.1

Type RM Length L Ch R = 1 ,35623   ,385.5,397.6,411.4
XS GIS Cut Line= 3
      1937487.83      203476.521     1937104.416      203620.303
     1936723.452      203770.693
#Sta/Elev= 30
       0 2527.45      40 2506.79    49.9 2497.48    59.9 2491.34   119.8 2461.07
   129.8  2454.7   139.8 2446.14   179.8 2426.54   209.7 2413.22   219.7 2405.02
   229.7 2398.61   299.6 2356.97   309.6 2348.76   319.6 2345.65   359.6  2338.8
   379.5 2333.34   389.5 2328.78   399.5 2326.46   401.6 2326.53   416.6 2327.58
   469.4 2333.88   529.4 2343.29   549.3 2347.66   629.3 2374.17   639.2 2378.24
   649.2 2384.49   669.2 2392.43   709.2 2404.02   729.2 2407.19   819.1 2437.68
#Mann= 3 , 0 , 0
       0      .1       0   401.6    .045       0   416.6      .1       0
Bank Sta=401.6,416.6
XS Rating Curve= 0 ,0
Exp/Cntr=0.3,0.1

Type RM Length L Ch R = 1 ,35225.3 ,417.7,413.7,408.4
XS GIS Cut Line= 3
     1937457.087      203304.363     1937047.716      203231.926
     1936650.061      203138.857
#Sta/Elev= 30
       0 2530.87     9.9 2525.08    19.8 2515.91    49.5 2500.67    89.1 2477.26
      99 2465.38   168.3 2423.25   178.2 2413.84   188.1 2407.22   247.5 2377.23
   267.3 2362.69   316.8 2338.98   346.4 2322.86   366.2 2318.25   395.9 2309.25
   405.8 2307.56   408.2 2307.64   423.2 2309.27   535.3 2318.59   555.2 2323.38
   575.1 2331.44     595    2344   624.9  2357.3   654.8 2372.45   674.7 2388.83
   734.5 2426.67   744.4 2434.21   754.4  2445.8   764.4 2446.42   824.1 2485.18
#Mann= 3 , 0 , 0
       0      .1       0   408.2    .045       0   423.2      .1       0
Bank Sta=408.2,423.2
XS Rating Curve= 0 ,0
Exp/Cntr=0.3,0.1

Type RM Length L Ch R = 1 ,34811.5 ,366.8,375.1,384.9
XS GIS Cut Line= 3
     1937502.848      202832.405     1936969.479      202833.503
     1936678.727      202950.989
#Sta/Elev= 30
       0 2481.81    29.6 2463.59    59.3 2447.13      79  2432.4   138.3 2404.54
     158 2390.32   217.3 2361.95     237 2348.05   296.3 2319.26   306.2 2313.23
   316.1 2304.93   335.8 2296.29   345.7 2293.81     403 2287.76   414.8    2287
     418 2287.06   434.6 2288.64   464.2 2295.53   474.1 2299.97   493.9    2304
   562.8 2315.06   631.4 2328.74   690.2 2350.01   719.6 2363.96   729.4 2372.07
   739.2 2376.66     798 2398.76   817.6 2404.82   827.4 2411.55     847 2420.17
#Mann= 3 , 0 , 0
       0      .1       0     403    .045       0     418      .1       0
Bank Sta=403,418
XS Rating Curve= 0 ,0
Exp/Cntr=0.3,0.1

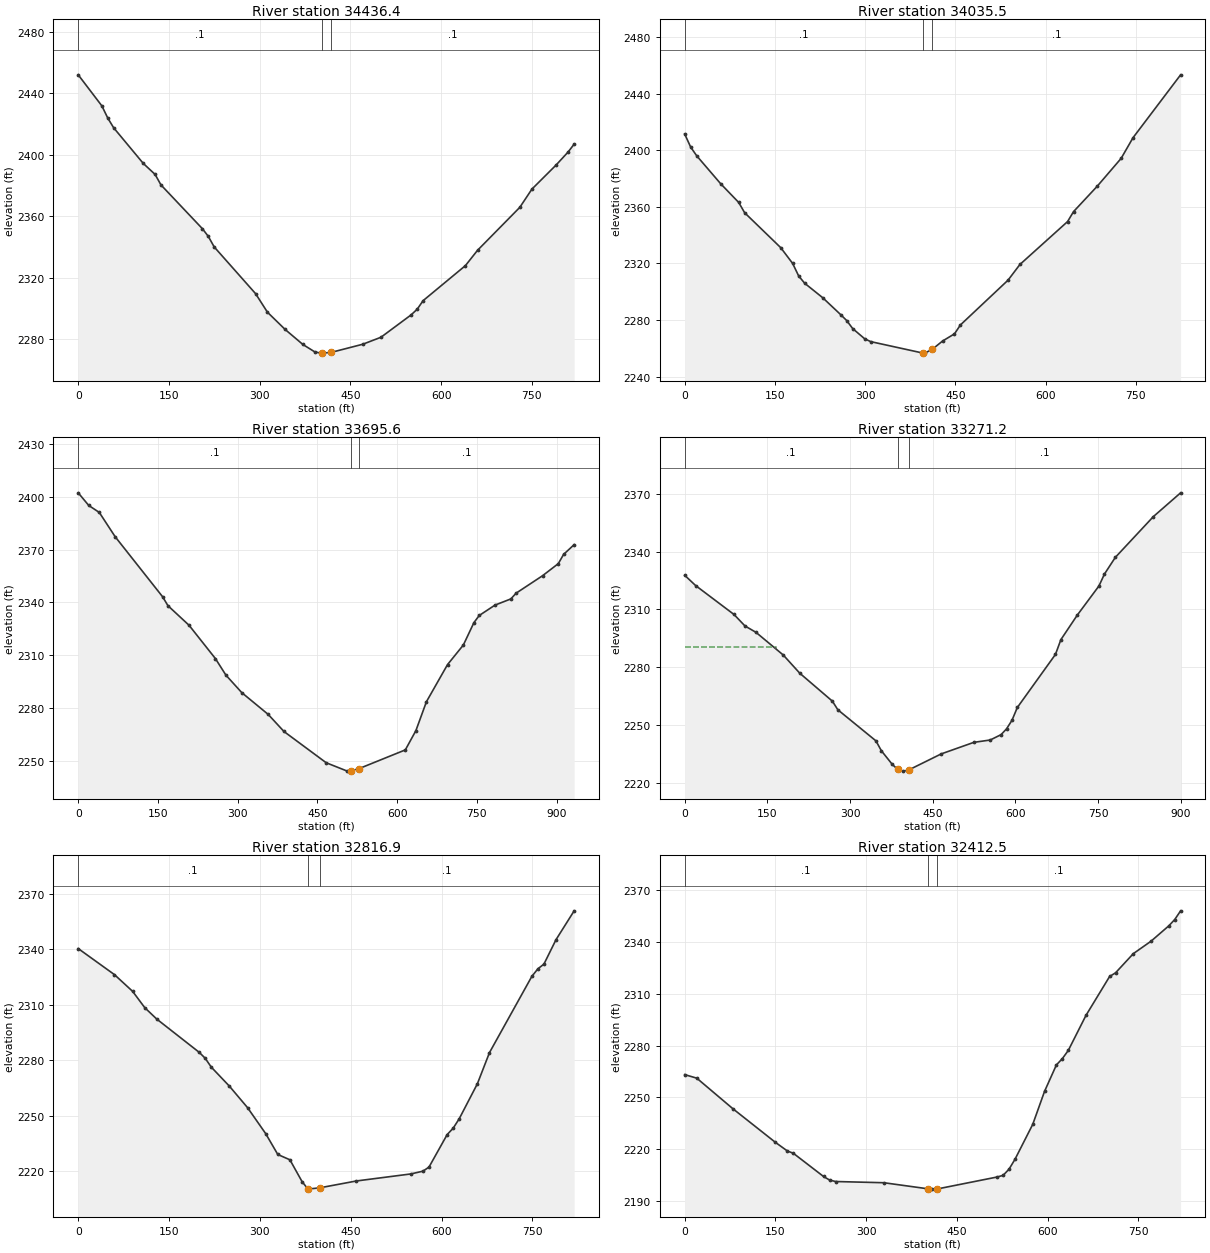
Type RM Length L Ch R = 1 ,34436.4 ,397.2,399.6,402.4
XS GIS Cut Line= 3
     1937558.111      202617.331     1937173.807      202472.997
     1936800.576      202304.943
#Sta/Elev= 30
       0 2452.06    39.1 2431.83    48.9 2423.86    58.6 2417.56   107.5 2394.37
   127.1 2387.18   136.8 2380.34   205.3 2351.81     215 2346.84   224.8 2339.94
   293.2 2309.51   312.8 2297.43   342.1 2286.17   371.4  2276.4     391 2271.59
   400.7 2270.77     403 2270.79     418 2271.23   470.4 2276.56   500.4  2281.1
   550.3 2295.68   560.3 2299.36   570.2 2304.98   640.1 2327.79   660.1 2337.76
     730 2365.75     750 2377.62   789.9 2393.28   809.8 2401.78   819.8 2406.92
#Mann= 3 , 0 , 0
       0      .1       0     403    .045       0     418      .1       0
Bank Sta=403,418
XS Rating Curve= 0 ,0
Exp/Cntr=0.3,0.1

Type RM Length L Ch R = 1 ,34035.5 ,339.4,339.5,337.8
XS GIS Cut Line= 3
     1937669.948      202287.628      1937301.35      202110.567
     1936947.672      201892.502
#Sta/Elev= 30
       0 2411.43      10 2402.15      20 2396.02    59.8  2376.3    89.8 2363.08
    99.7 2355.79   159.6 2331.16   179.5 2319.98   189.5 2311.12   199.5 2305.98
   229.4 2295.79   259.3 2283.83   269.3 2279.65   279.3 2273.96   299.2 2266.76
   309.2 2264.76   396.3 2256.64     399 2256.63   411.3 2259.23   428.7 2265.18
   448.5 2270.25   458.4 2276.55   537.5 2308.16   557.3 2319.26   636.5 2349.56
   646.4 2356.57   685.9 2374.58   725.5 2394.19   745.3 2408.81   824.4 2453.22
#Mann= 3 , 0 , 0
       0      .1       0   396.3    .045       0   411.3      .1       0
Bank Sta=396.3,411.3
XS Rating Curve= 0 ,0
Exp/Cntr=0.3,0.1

Type RM Length L Ch R = 1 ,33695.6 ,426.9,423.6,418.3
XS GIS Cut Line= 3
      1937872.04      202121.134     1937557.436      201862.946
     1937083.785      201634.122
#Sta/Elev= 30
       0 2402.28    19.8 2395.11    39.7 2391.12    69.5 2377.33   158.8 2343.18
   168.8 2338.11   208.5 2326.99   258.1 2308.05   277.9 2298.63   307.7 2288.69
   357.4 2276.31   387.1 2266.59   466.5 2248.83   506.2 2244.06   513.3 2244.19
   528.3 2245.49   615.4 2256.13   635.3  2267.1   655.1 2283.52   694.8 2304.63
   724.6 2315.78   744.4 2328.46   754.4 2332.54   784.1 2338.45   813.9 2341.96
   823.8 2345.23   873.5 2355.14   903.2 2362.03   913.2  2367.3     933 2372.82
#Mann= 3 , 0 , 0
       0      .1       0   513.3    .045       0   528.3      .1       0
Bank Sta=513.3,528.3
XS Rating Curve= 0 ,0
Exp/Cntr=0.3,0.1

Type RM Length L Ch R = 1 ,33271.2 ,440.8,454.4,467.9
XS GIS Cut Line= 3
     1938083.373      201611.311     1937887.238      201539.696
     1937204.717      201432.016
#Sta/Elev= 30
       0  2327.8    19.9 2322.43    89.5  2307.4   109.4 2301.43   129.3 2298.13
     179 2286.28   208.8 2276.86     268 2262.32   277.9 2257.84     347 2241.68
   356.9 2236.52   376.6 2229.46   386.5 2226.82   396.4 2225.94   406.2 2226.51
   465.4 2234.89   524.7 2240.91   554.3 2242.12     574 2244.91   583.9 2247.89
   593.8 2252.36   603.6 2259.05   672.7 2286.63   682.6 2294.33   712.2 2307.02
   751.7 2322.26   761.6 2328.42   781.3 2337.08   850.4 2358.31   899.8 2370.66
#Mann= 3 , 0 , 0
       0      .1       0   386.5    .045       0   406.2      .1       0
#XS Ineff= 2 , 0
          165.07 2290.58
Permanent Ineff=
       F       F
Bank Sta=386.5,406.2
XS Rating Curve= 0 ,0
Exp/Cntr=0.3,0.1

Type RM Length L Ch R = 1 ,32816.9 ,406.6,404.4,403.9
XS GIS Cut Line= 3
     1938218.141      201460.036     1937921.926      201177.287
     1937625.712      200894.537
#Sta/Elev= 30
       0 2340.29    59.9 2326.18    89.9 2317.14   109.9 2308.33   129.8 2302.14
   199.8 2284.19   209.7 2280.98   219.7  2276.2   249.7 2265.88   279.7 2254.25
   309.6 2240.23   329.6 2228.95   349.6 2226.08   369.6 2214.32   379.5 2210.22
   399.5 2210.96   459.4 2214.63   549.3 2218.43   569.3 2219.93   579.3 2222.14
   609.3 2239.72   619.2 2243.16   629.2 2248.27   659.2 2267.19   679.2 2284.05
   749.1 2325.23   759.1 2329.34   769.1 2331.88     789 2345.07     819 2360.69
#Mann= 3 , 0 , 0
       0      .1       0   379.5    .045       0   399.5      .1       0
Bank Sta=379.5,399.5
XS Rating Curve= 0 ,0
Exp/Cntr=0.3,0.1

Type RM Length L Ch R = 1 ,32412.5 ,404.1,412.3,418.8
XS GIS Cut Line= 3
     1938516.736      201140.327     1938194.232       200888.37
     1937890.157      200612.039
#Sta/Elev= 30
       0 2263.21      20 2261.16    79.9 2243.43   149.7 2224.13   169.7 2219.07
   179.7 2217.72   229.6  2204.3   239.6 2202.25   249.6 2201.39   329.4 2200.69
   401.8  2197.2   409.3 2196.99   416.8 2197.03   516.9 2204.01   526.6 2204.97
   536.4 2208.55   546.2 2214.24   575.6 2234.46   595.1 2253.54   614.7 2268.82
   624.5 2272.44   634.3 2277.16   663.6 2297.46   702.7 2319.96   712.5 2322.07
   741.9 2333.17   771.2 2340.36   800.6 2349.25   810.4  2352.9   820.1 2357.92
#Mann= 3 , 0 , 0
       0      .1       0   401.8    .045       0   416.8      .1       0
Bank Sta=401.8,416.8
XS Rating Curve= 0 ,0
Exp/Cntr=0.3,0.1

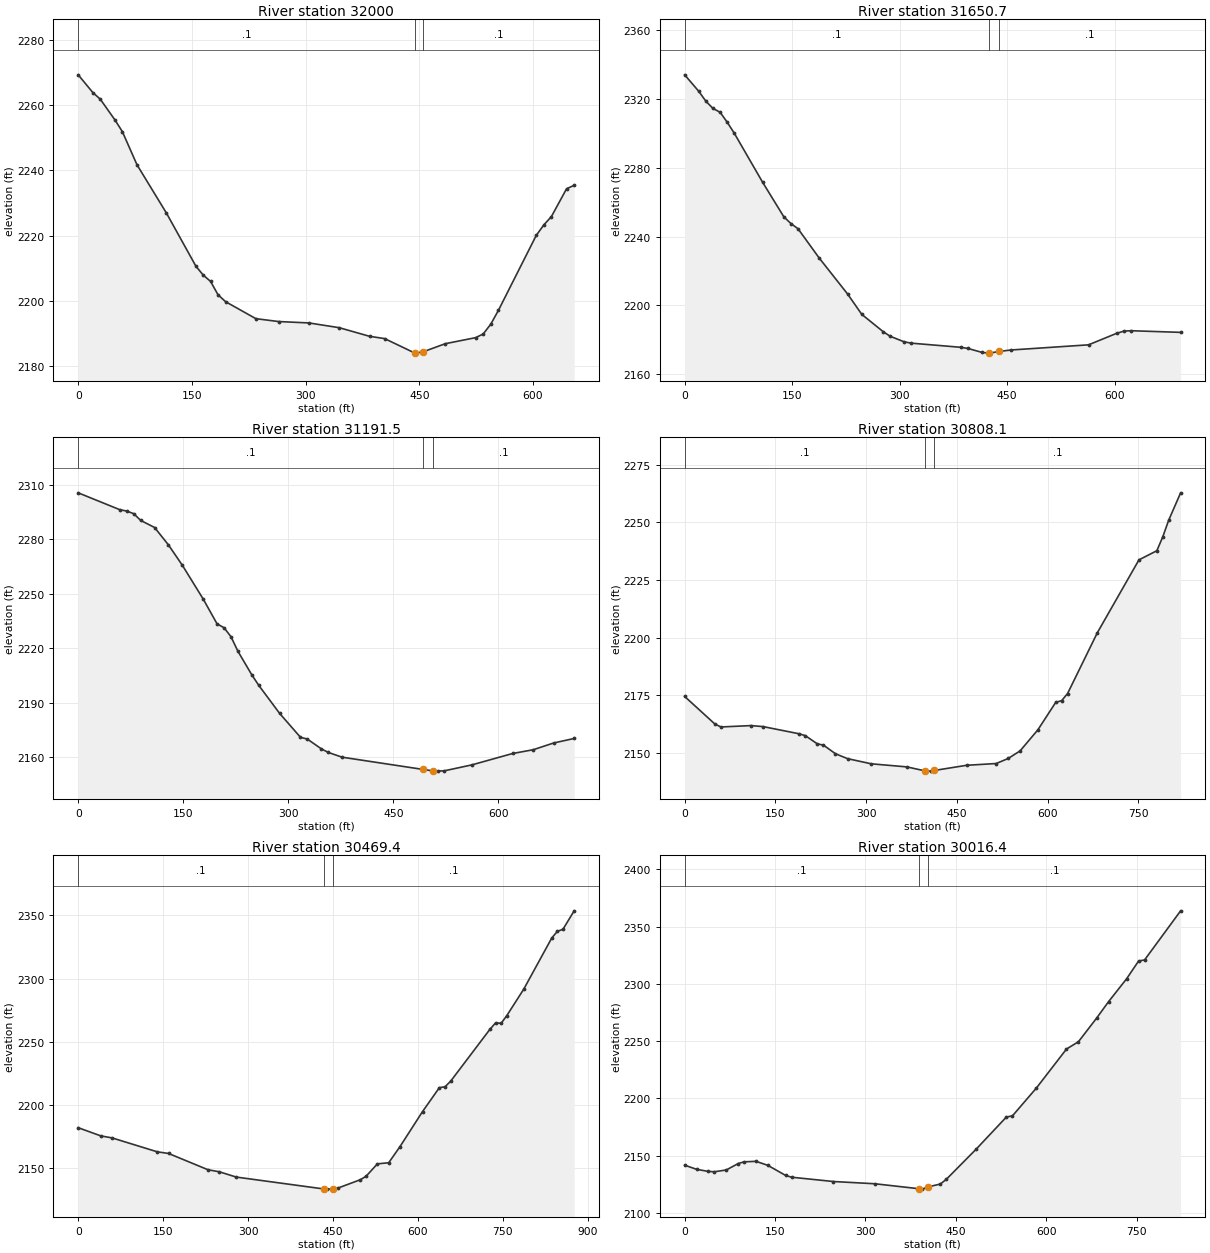
Type RM Length L Ch R = 1 ,32000   ,345.8,349.5,353.1
XS GIS Cut Line= 3
     1938752.634      200961.531     1938621.114      200832.326
     1938375.936      200431.427
#Sta/Elev= 30
       0 2269.28    19.4 2263.82    29.1 2261.82    48.5 2255.44    58.2 2251.89
    77.6 2241.69   116.4 2226.91   155.3 2210.62     165 2207.89   174.7 2205.95
   184.4 2201.89   194.4 2199.76   234.4 2194.55   264.4 2193.67   304.4 2193.24
   344.3 2191.79   384.3 2189.15   404.3 2188.44   444.3 2183.99   454.3 2184.33
   484.3 2186.88   524.3 2188.73   534.3 2189.86   544.3 2192.86   554.3 2197.06
   604.3 2220.07   614.3 2223.29   624.3 2225.84   644.3 2234.37   654.3 2235.41
#Mann= 3 , 0 , 0
       0      .1       0   444.3    .045       0   454.3      .1       0
Bank Sta=444.3,454.3
XS Rating Curve= 0 ,0
Exp/Cntr=0.3,0.1

Type RM Length L Ch R = 1 ,31650.7 ,471.8,458.5,445.2
XS GIS Cut Line= 2
     1938949.024      200894.153     1938707.257      200245.888
#Sta/Elev= 30
       0 2334.06    19.8  2324.4    29.6 2318.71    39.5 2314.51    49.4 2312.31
    59.3 2306.53    69.2 2300.11   108.7 2271.62   138.4 2251.47   148.3 2247.57
   158.1 2244.58   187.8 2227.48   227.3 2206.61   247.1 2194.78   276.8 2184.77
   286.6 2182.07   306.4 2178.79   316.3 2178.04   385.5 2175.63   395.4 2174.95
   415.1 2172.64   424.2 2172.28     425 2172.25   439.2 2173.23   454.7 2174.06
   563.4 2177.07   602.9  2183.8   612.8 2185.06   622.7 2185.28   691.9 2184.32
#Mann= 3 , 0 , 0
       0      .1       0   424.2    .045       0   439.2      .1       0
Bank Sta=424.2,439.2
XS Rating Curve= 0 ,0
Exp/Cntr=0.3,0.1

Type RM Length L Ch R = 1 ,31191.5 ,378.8,383.1,387.3
XS GIS Cut Line= 3
     1939451.072      200648.443     1939248.967      200330.375
      1938978.94      200138.209
#Sta/Elev= 30
       0  2305.5    59.5 2296.21    69.4 2295.46    79.3 2294.03    89.2 2290.34
   109.1 2286.43   128.9 2276.85   148.8 2265.62   178.5  2247.1   198.3 2233.45
   208.3 2231.32   218.2 2226.37   228.1 2218.37   247.9 2205.43   257.8 2199.67
   287.6 2184.25   317.4 2171.09   327.3 2170.08   347.1 2164.76     357 2162.77
   376.8 2160.14   492.4 2153.41   507.4 2152.59   513.3 2152.47   523.1 2152.66
   562.1 2155.89   620.5 2162.17   649.8 2164.23     679 2167.94   708.3 2170.43
#Mann= 3 , 0 , 0
       0      .1       0   492.4    .045       0   507.4      .1       0
Bank Sta=492.4,507.4
XS Rating Curve= 0 ,0
Exp/Cntr=0.3,0.1

Type RM Length L Ch R = 1 ,30808.1 ,323.3,338.7,354
XS GIS Cut Line= 3
      1939690.07      200369.986     1939537.216      200148.148
     1939156.197      199750.563
#Sta/Elev= 30
       0 2174.46    49.9 2162.52    59.9 2161.23   109.8 2161.83   129.7 2161.39
   189.6 2158.26   199.6 2157.44   219.5 2153.88   229.5 2153.36   249.4  2149.6
   269.4 2147.48   308.7 2145.24   367.7  2143.9   397.9 2142.14   407.1 2142.07
   412.9 2142.36   466.1  2144.6   515.2 2145.37   534.9 2147.55   554.6 2150.84
   584.1    2160   613.6 2171.92   623.4 2172.65   633.2 2175.75   682.4 2202.12
   751.2 2233.74   780.8  2237.7   790.6 2243.72   800.4 2250.96   820.1 2262.82
#Mann= 3 , 0 , 0
       0      .1       0   397.9    .045       0   412.9      .1       0
Bank Sta=397.9,412.9
XS Rating Curve= 0 ,0
Exp/Cntr=0.3,0.1

Type RM Length L Ch R = 1 ,30469.4 ,459.4,452.9,445.6
XS GIS Cut Line= 3
     1939767.484      200333.688     1939702.876      199729.027
     1939798.366      199478.909
#Sta/Elev= 30
       0 2181.79    39.9  2175.3    59.8 2173.71   139.6 2162.68   159.5 2161.38
   229.3 2148.46   249.2 2146.86   279.1 2142.67   434.3 2133.22   438.6 2133.12
   449.3 2133.26   458.6 2133.94   498.4 2140.61   508.4 2143.33   528.4 2153.16
   548.3 2154.01   568.2 2166.78   608.1 2194.61   637.8 2213.53   647.8 2214.22
   657.7 2218.65   727.1 2259.77     737  2264.8   746.9 2264.54   756.8 2270.56
   786.6 2291.42   836.2 2332.06   846.1 2337.38     856 2338.98   875.8 2353.63
#Mann= 3 , 0 , 0
       0      .1       0   434.3    .045       0   449.3      .1       0
Bank Sta=434.3,449.3
XS Rating Curve= 0 ,0
Exp/Cntr=0.3,0.1

Type RM Length L Ch R = 1 ,30016.4 ,419.8,419.8,420.1
XS GIS Cut Line= 3
     1940286.509      200179.518     1940117.321      199801.514
     1939909.174      199449.672
#Sta/Elev= 30
       0 2141.65    19.7 2138.07    39.4 2136.19    49.3 2135.93      69 2137.47
    88.7 2143.06    98.6 2144.59   118.3 2145.03     138 2141.52   167.6 2132.68
   177.5 2131.15   246.5 2127.41   315.5 2125.44   389.2 2121.08   394.4 2120.75
   404.2 2122.75   424.1 2125.17   434.1  2129.3   483.9  2155.8   533.8 2183.73
   543.8 2184.71   583.6 2209.06   633.5 2243.09   653.4 2249.51   683.4 2270.04
   703.3 2284.46   733.2 2304.42   753.2    2320   763.1 2320.93   822.9 2363.83
#Mann= 3 , 0 , 0
       0      .1       0   389.2    .045       0   404.2      .1       0
Bank Sta=389.2,404.2
XS Rating Curve= 0 ,0
Exp/Cntr=0.3,0.1

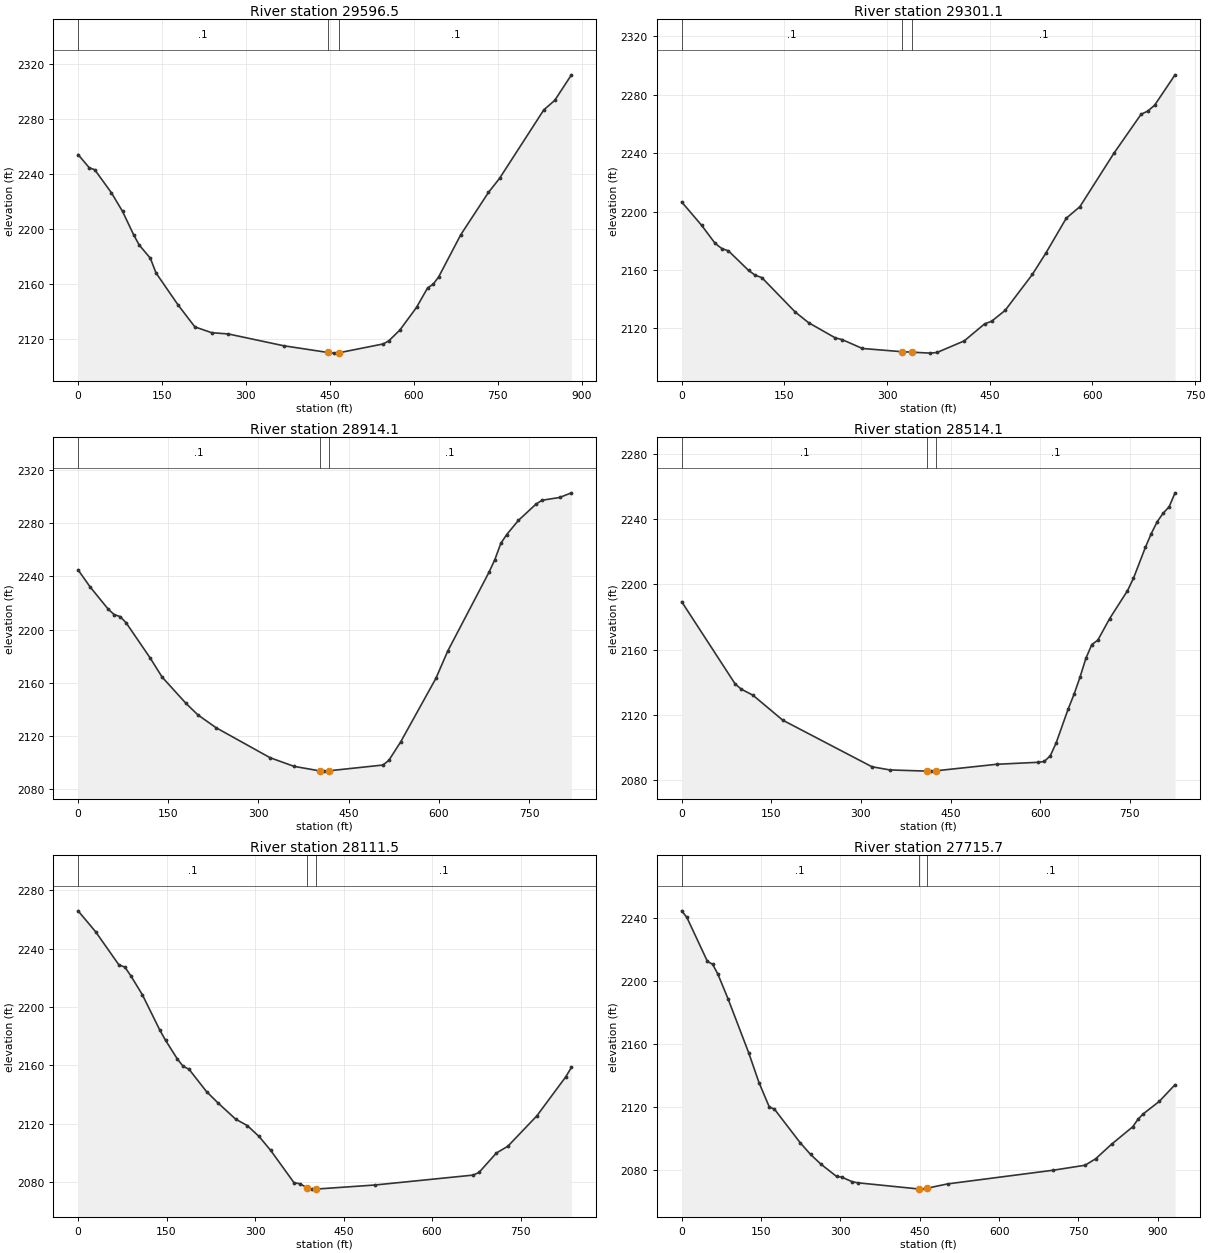
Type RM Length L Ch R = 1 ,29596.5 ,300.9,295,289.3
XS GIS Cut Line= 3
     1940696.839      200146.492     1940577.563      199851.616
     1940347.072      199337.396
#Sta/Elev= 30
       0 2254.26    19.9 2244.66    29.8 2243.17    59.6 2226.41    79.5 2212.82
    99.4 2195.74   109.3 2188.34   129.2 2178.74   139.2  2168.1   178.9 2144.64
   208.7 2128.77   238.6 2124.56   268.4 2123.63   367.5 2115.03   446.6 2110.14
   456.5 2109.67   466.4 2109.95   545.5 2116.38   555.4 2118.66   575.1 2126.53
   604.8 2142.96   624.6 2157.17   634.4 2159.79   644.3 2165.14   683.9 2195.91
   733.3 2226.66   753.1 2236.88   832.2 2286.75   851.9 2293.76   881.6 2312.29
#Mann= 3 , 0 , 0
       0      .1       0   446.6    .045       0   466.4      .1       0
Bank Sta=446.6,466.4
XS Rating Curve= 0 ,0
Exp/Cntr=0.3,0.1

Type RM Length L Ch R = 1 ,29301.1 ,395.2,386.9,377.4
XS GIS Cut Line= 3
      1940925.45       199844.99     1940786.295       199644.54
     1940517.756      199250.708
#Sta/Elev= 30
       0 2206.58    29.3 2190.46    48.8 2178.21    58.6 2174.64    68.3 2173.06
    97.6 2159.71   107.4 2156.34   117.1 2154.72   165.9 2131.12   185.4 2123.82
   224.5 2113.38   234.3 2112.27   263.9 2106.17   321.5 2103.95   336.5 2103.62
   363.2 2102.97   373.1 2103.43   412.8 2111.37   442.6 2123.06   452.6 2124.77
   472.4 2132.22   512.2 2156.86     532 2171.54   561.8 2195.44   581.7 2203.34
   631.3 2239.88     671 2266.63     681  2268.9   690.9  2272.9   720.7  2293.7
#Mann= 3 , 0 , 0
       0      .1       0   321.5    .045       0   336.5      .1       0
Bank Sta=321.5,336.5
XS Rating Curve= 0 ,0
Exp/Cntr=0.3,0.1

Type RM Length L Ch R = 1 ,28914.1 ,392.7,400,411.6
XS GIS Cut Line= 3
     1941332.024      199505.203     1940984.679      199289.209
     1940625.255      199089.004
#Sta/Elev= 30
       0 2244.86      20 2232.05    49.9 2215.44    59.9 2211.26    69.8 2209.77
    79.8 2205.14   119.7 2178.72   139.7 2164.28   179.6 2144.39   199.5 2135.73
   229.4 2126.19   319.2 2103.63   359.1 2097.11   401.5 2093.74     409 2093.52
   416.5 2093.75     507  2098.1   516.8 2101.65   536.4 2115.48   595.1 2163.36
   614.7  2183.8   683.3 2243.06   693.1 2252.64   702.9  2264.7   712.7 2271.39
   732.3 2282.11   761.7 2294.39   771.5 2297.21   800.8 2299.32   820.4  2302.8
#Mann= 3 , 0 , 0
       0      .1       0   401.5    .045       0   416.5      .1       0
Bank Sta=401.5,416.5
XS Rating Curve= 0 ,0
Exp/Cntr=0.3,0.1

Type RM Length L Ch R = 1 ,28514.1 ,394.4,402.3,403.8
XS GIS Cut Line= 3
     1941456.045      199276.379     1941187.697      198956.175
     1940972.272      198609.742
#Sta/Elev= 30
       0 2189.38    89.5 2138.82    99.5 2135.68   119.4 2131.86   169.1 2116.56
   318.3 2087.94   348.2 2085.97   410.3 2085.24   417.8 2085.23   425.3 2085.43
   527.2 2089.44   596.9 2090.67   606.8 2091.16   616.8  2094.6   626.7 2102.57
   646.6 2123.19   656.6 2132.42   666.5 2142.82   676.5 2154.58   686.4 2163.07
   696.4 2165.71   716.3 2179.04   746.1 2196.14   756.1 2203.79     776 2222.74
   785.9 2231.28   795.9 2238.58   805.8  2243.8   815.8 2247.76   825.7 2256.32
#Mann= 3 , 0 , 0
       0      .1       0   410.3    .045       0   425.3      .1       0
Bank Sta=410.3,425.3
XS Rating Curve= 0 ,0
Exp/Cntr=0.3,0.1

Type RM Length L Ch R = 1 ,28111.5 ,401.5,395.7,393
XS GIS Cut Line= 3
     1941687.958      199174.788      1941548.48      198793.812
     1941310.154      198435.225
#Sta/Elev= 30
       0 2266.03    29.7 2251.69    69.3 2228.88    79.2 2227.44    89.1 2221.62
   108.8 2208.55   138.5 2184.21   148.4 2177.05   168.2 2164.37   178.1 2159.28
     188 2157.32   217.7 2141.95   237.5 2134.04   267.2    2123     287 2118.58
   306.8 2111.12   326.5 2101.57   366.1 2079.34     376 2078.68   388.6 2075.87
   395.8 2074.98   403.6 2075.02   503.6 2077.82   669.9 2084.62   679.7 2086.47
   709.1 2099.77   728.6 2104.45   777.6 2125.24   826.5 2151.97   836.3 2158.56
#Mann= 3 , 0 , 0
       0      .1       0   388.6    .045       0   403.6      .1       0
Bank Sta=388.6,403.6
XS Rating Curve= 0 ,0
Exp/Cntr=0.3,0.1

Type RM Length L Ch R = 1 ,27715.7 ,417.9,418.6,419.3
XS GIS Cut Line= 3
     1942063.142      198866.219     1941887.937      198657.204
     1941513.545      198113.838
#Sta/Elev= 30
       0 2244.48     9.7 2240.37    48.7 2212.34    58.4 2210.58    68.2 2204.46
    87.7 2188.58   126.6 2154.46   146.1  2135.5   165.6 2119.99   175.3 2118.63
     224 2097.31   243.5  2089.9     263 2083.77   292.7 2075.92   302.7 2075.46
   322.7  2072.5   332.7 2071.89   447.9 2067.97   452.7 2067.86   462.9 2068.38
   502.7 2071.18   702.6 2079.87   762.6 2083.03   782.6 2087.14   812.6 2096.36
   852.6 2107.42   862.6 2112.24   872.6 2115.66   902.6 2123.48   932.6 2134.15
#Mann= 3 , 0 , 0
       0      .1       0   447.9    .045       0   462.9      .1       0
Bank Sta=447.9,462.9
XS Rating Curve= 0 ,0
Exp/Cntr=0.3,0.1