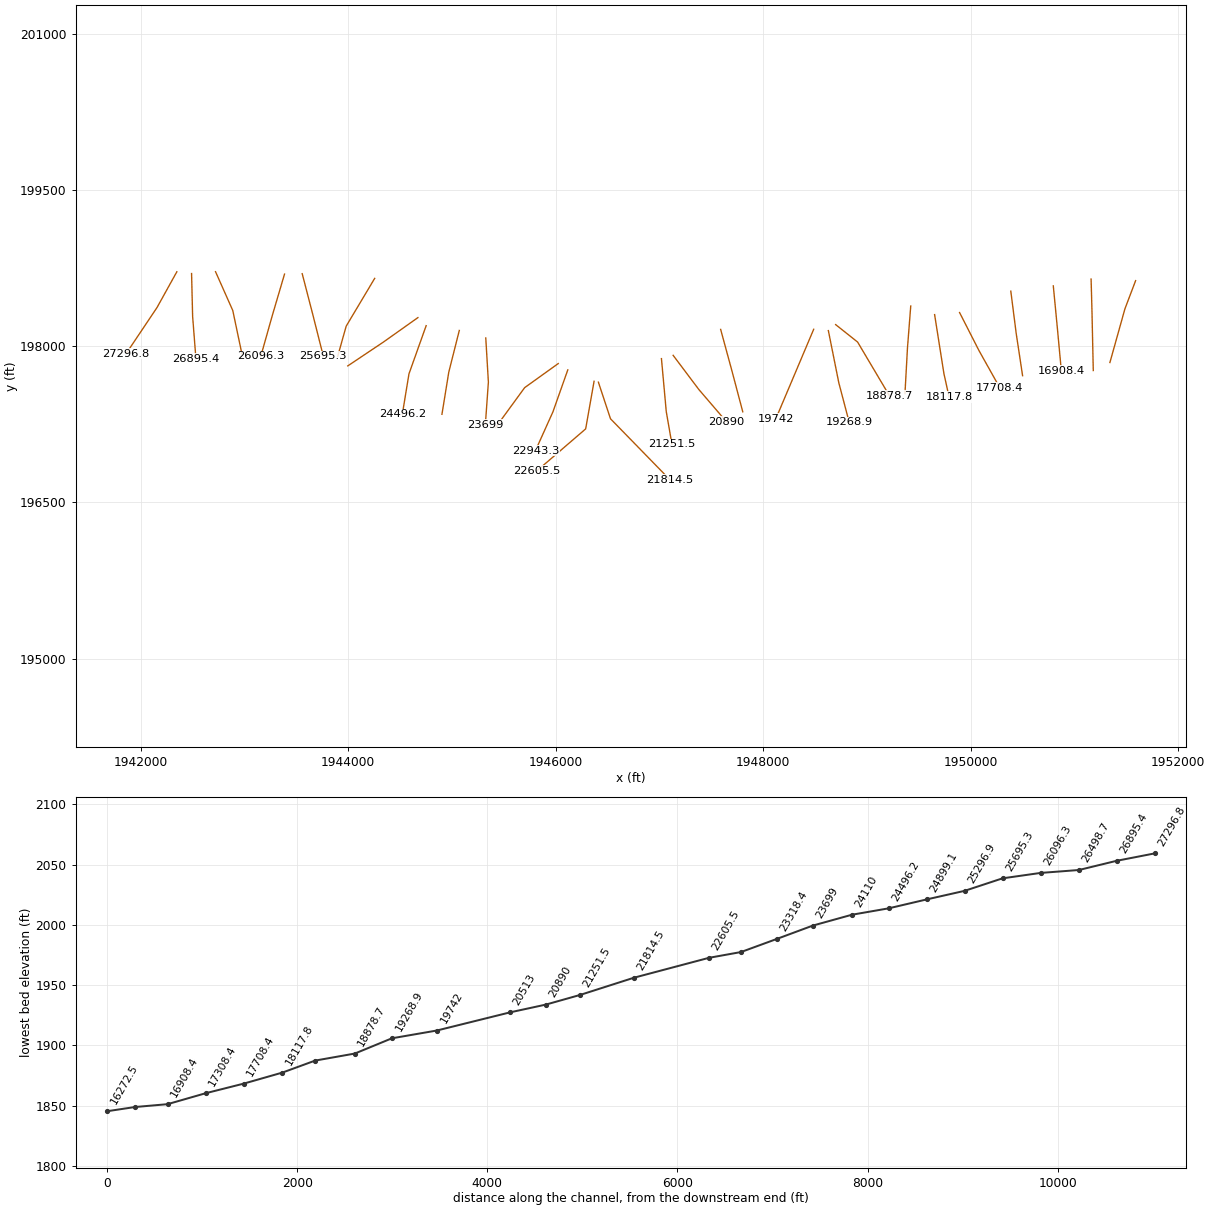
HEC-RAS study MntnCrk.prj: MntnCrk

--- MntnCrk.g01 (geometry) --- (continued)

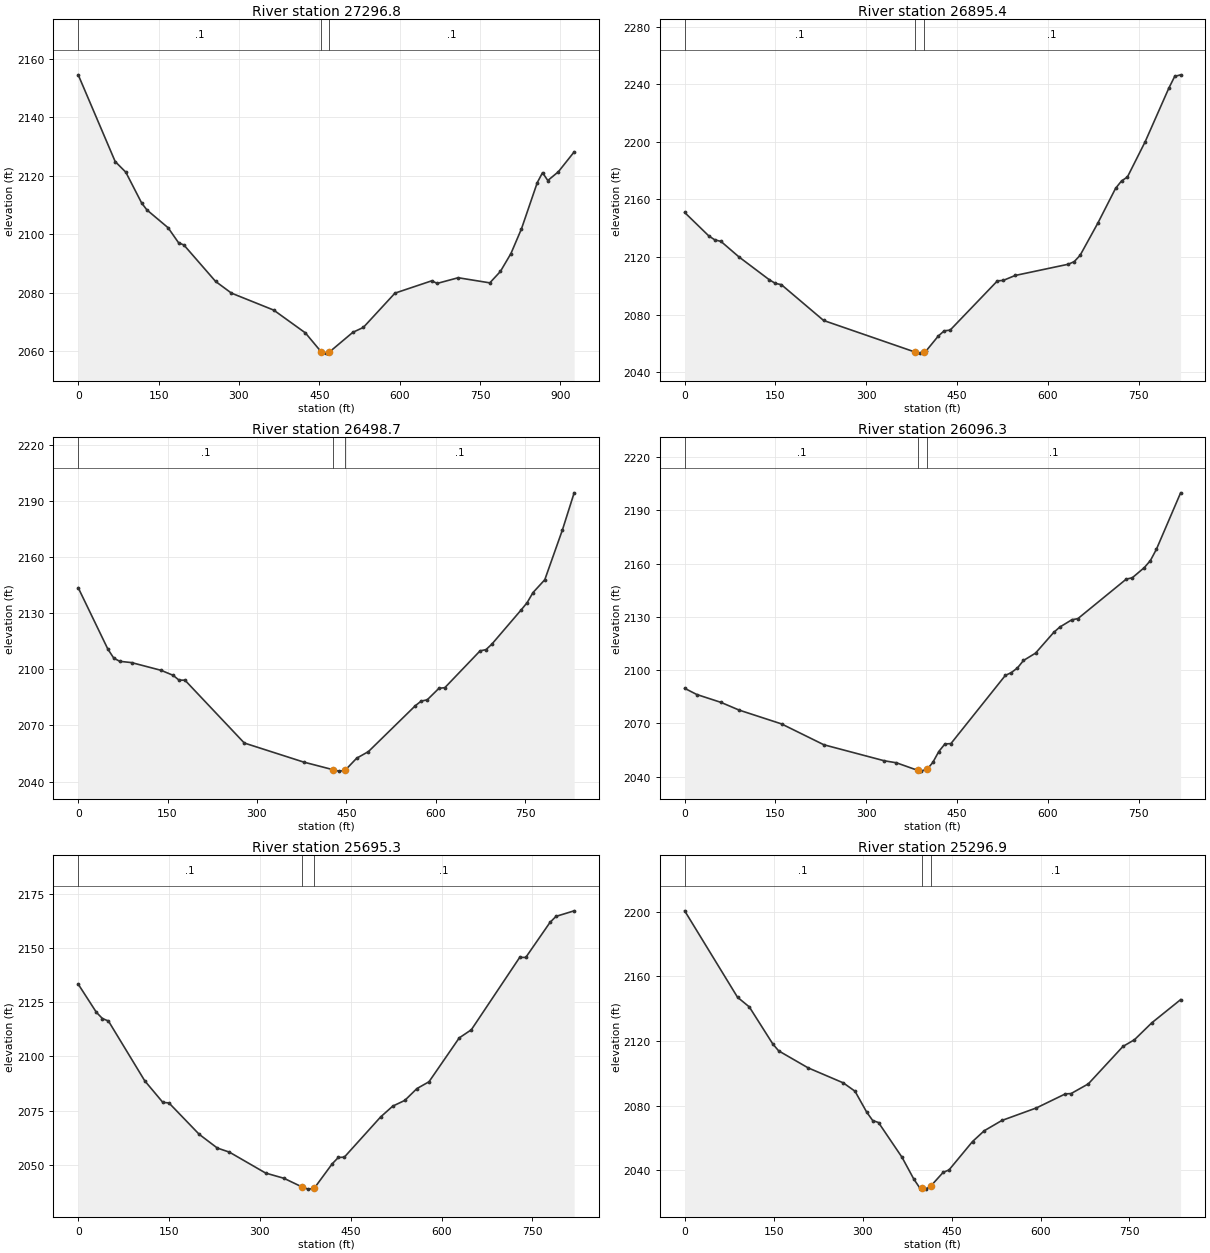
Type RM Length L Ch R = 1 ,27296.8 ,387,400.9,414.9
XS GIS Cut Line= 3
     1942350.029      198713.525     1942157.964      198368.955
     1941861.431      197928.299
#Sta/Elev= 30
       0 2154.43      69  2124.8    88.8 2121.17   118.4 2110.63   128.2 2108.27
   167.7 2102.19   187.4 2097.03   197.2  2096.3   256.4 2083.84     286 2079.84
   364.9 2074.04     424 2066.25   453.5 2059.78   463.3 2059.34   468.5 2059.67
   512.5 2066.44   532.2 2068.13   591.2 2079.84     660 2084.06   669.9 2083.16
   709.2  2085.1   768.2 2083.35   787.9 2087.24   807.6 2093.36   827.3 2101.83
   856.8 2117.62   866.6    2121   876.4 2118.32   896.1  2121.3   925.6 2128.09
#Mann= 3 , 0 , 0
       0      .1       0   453.5    .045       0   468.5      .1       0
Bank Sta=453.5,468.5
XS Rating Curve= 0 ,0
Exp/Cntr=0.3,0.1

Type RM Length L Ch R = 1 ,26895.4 ,387.7,396.6,400.3
XS GIS Cut Line= 3
     1942491.967      198696.735     1942502.072      198287.482
     1942533.839      197878.519
#Sta/Elev= 30
       0 2150.95    39.9 2134.65    49.9 2131.89    59.9 2130.87    89.9    2120
   139.8 2104.21   149.8 2101.67   159.8 2100.78   229.6 2075.89   380.2 2054.01
   389.4 2053.19   395.2  2054.2   399.4 2054.94   419.1 2065.06   428.9 2068.68
   438.7 2069.18   516.8  2103.4   526.6 2103.75   546.1 2107.16     634 2114.98
   643.8  2116.8   653.5 2121.18   682.8 2143.56   712.1 2167.72   721.9 2172.85
   731.7 2175.63     761 2200.12     800 2237.27   809.8 2245.52   819.6 2246.63
#Mann= 3 , 0 , 0
       0      .1       0   380.2    .045       0   395.2      .1       0
Bank Sta=380.2,395.2
XS Rating Curve= 0 ,0
Exp/Cntr=0.3,0.1

Type RM Length L Ch R = 1 ,26498.7 ,419,402.4,391.1
XS GIS Cut Line= 3
      1942722.88      198714.441     1942889.176      198341.663
     1942976.839      197926.495
#Sta/Elev= 30
       0  2143.7    49.8 2110.84    59.7 2106.04    69.7 2104.33    89.6 2103.64
   139.4 2099.48   159.3 2096.84   169.2 2094.26   179.2 2094.23   278.8  2060.6
   378.3 2050.42   427.9 2046.31   437.8 2045.56   447.7  2045.9   467.4 2052.47
   487.1    2056   566.1 2080.63   575.9 2083.07   585.8  2083.7   605.6  2089.9
   615.4 2090.22   674.6 2109.93   684.5 2110.58   694.4 2113.54   743.7 2131.89
   753.6 2135.74   763.4 2141.11   783.2 2147.99   812.8 2174.64   832.5  2194.5
#Mann= 3 , 0 , 0
       0      .1       0   427.9    .045       0   447.7      .1       0
Bank Sta=427.9,447.7
XS Rating Curve= 0 ,0
Exp/Cntr=0.3,0.1

Type RM Length L Ch R = 1 ,26096.3 ,388.3,400.9,413.3
XS GIS Cut Line= 3
     1943387.739      198691.292     1943271.189      198298.286
     1943159.583      197904.262
#Sta/Elev= 30
       0 2089.78      20  2086.3      60 2081.86      90 2077.52     160 2069.74
     230 2057.99   329.9 2048.97   349.9 2047.84   385.6 2043.52   389.9 2043.15
   400.6 2044.19   409.9 2048.02   419.9  2054.2   429.9 2058.43   439.9 2058.66
   529.8 2097.05   539.8 2098.66   549.8 2101.26   559.8 2105.46   579.7  2109.6
   609.7 2121.25   619.7 2124.26   639.7 2128.39   649.6 2129.01   729.6 2151.28
   739.5 2152.02   759.5 2157.79   769.5 2161.74   779.5 2168.16   819.4 2199.87
#Mann= 3 , 0 , 0
       0      .1       0   385.6    .045       0   400.6      .1       0
Bank Sta=385.6,400.6
XS Rating Curve= 0 ,0
Exp/Cntr=0.3,0.1

Type RM Length L Ch R = 1 ,25695.3 ,416.6,398.4,380.3
XS GIS Cut Line= 3
     1943558.103      198695.332     1943661.248      198299.036
     1943761.979      197902.109
#Sta/Elev= 30
       0 2133.43      30  2120.4      40 2117.52    49.9 2116.38   109.9 2088.72
   139.8 2078.74   149.8 2078.52   199.8 2063.99   229.7 2057.65   249.7 2055.75
   309.6 2046.07   339.6 2043.68   369.6 2039.66   379.5 2038.65   389.5 2038.95
   419.5 2050.37   429.5 2053.28   439.5 2053.44   499.4 2072.02   519.4 2077.02
   539.3 2079.67   559.3 2085.13   579.3 2088.29   629.2 2108.57   649.2 2112.33
   729.1  2145.8   739.1 2145.77   779.1 2161.96     789 2164.75     819 2167.32
#Mann= 3 , 0 , 0
       0      .1       0   369.6    .045       0   389.5      .1       0
Bank Sta=369.6,389.5
XS Rating Curve= 0 ,0
Exp/Cntr=0.3,0.1

Type RM Length L Ch R = 1 ,25296.9 ,407.7,397.6,387.5
XS GIS Cut Line= 3
     1944256.709       198650.54     1943981.885      198191.699
     1943899.922      197901.748
#Sta/Elev= 30
       0 2200.61    89.1  2147.1     109  2141.1   148.6 2118.16   158.5 2113.89
     208  2103.4   267.4 2094.08   287.2  2088.9     307  2075.9     317 2070.77
   326.8 2069.52   366.5 2047.97   386.3 2034.52   396.2 2029.14   399.5 2028.85
   406.1 2028.28   414.5    2030   435.8 2038.65   445.7 2040.16   485.3 2057.73
   505.1 2064.43   534.8 2070.79   593.2 2078.59   641.8 2087.25   651.5 2087.45
   680.6 2093.46     739 2116.64   758.4  2120.8   787.6 2131.26   836.2 2145.62
#Mann= 3 , 0 , 0
       0      .1       0   399.5    .045       0   414.5      .1       0
Bank Sta=399.5,414.5
XS Rating Curve= 0 ,0
Exp/Cntr=0.3,0.1

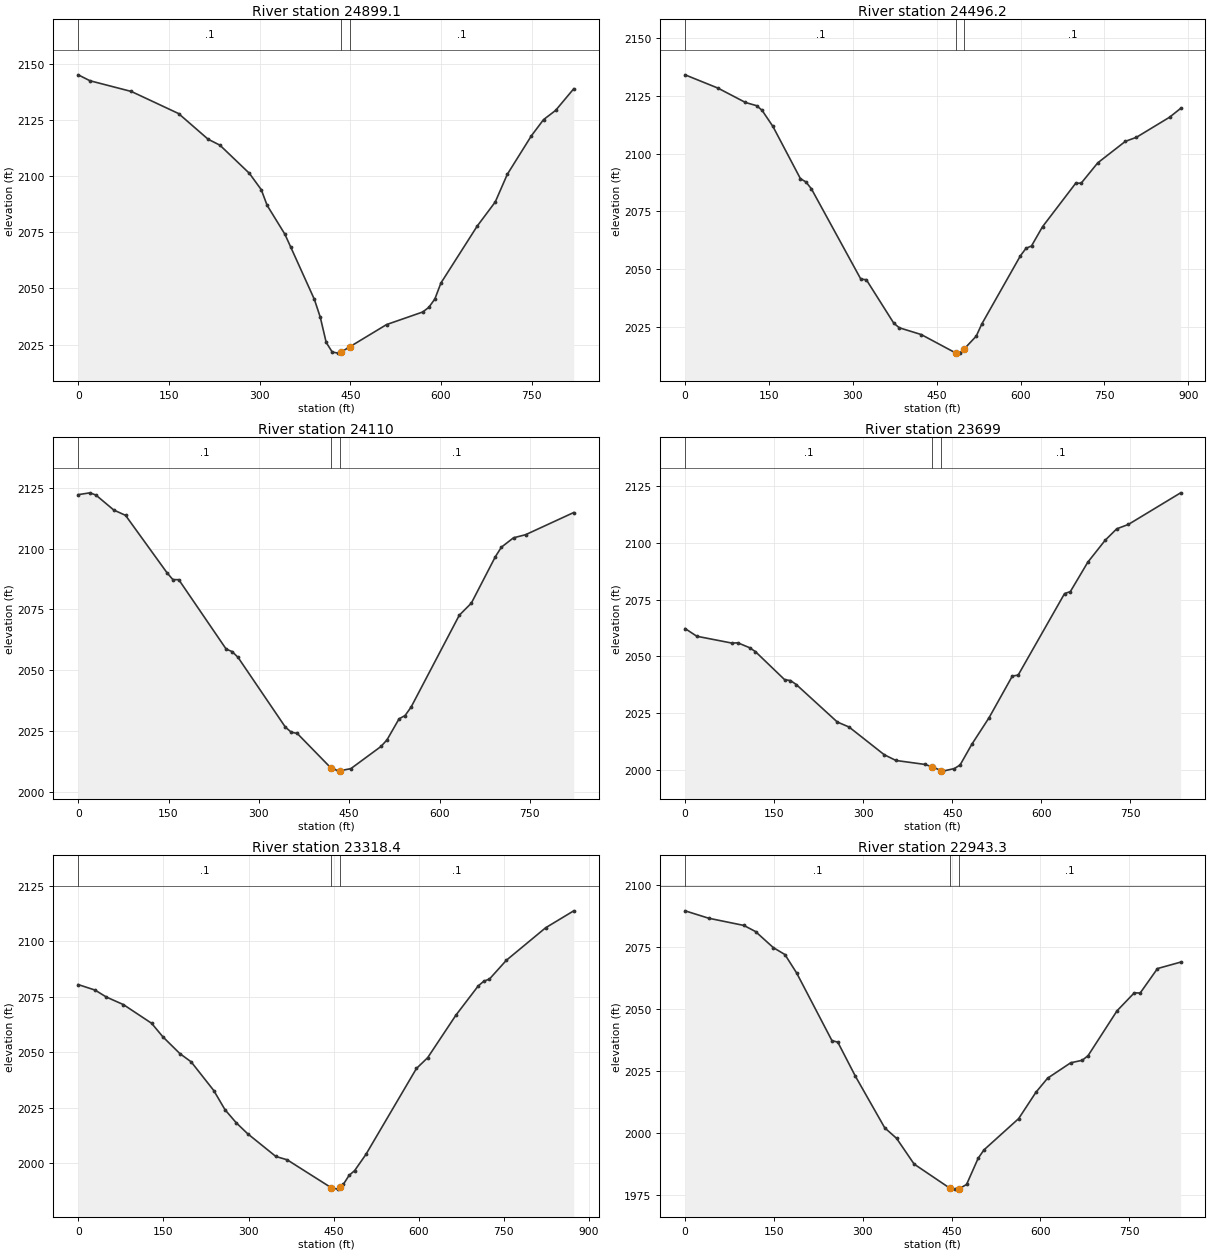
Type RM Length L Ch R = 1 ,24899.1 ,387.9,402.3,420.9
XS GIS Cut Line= 3
     1944673.122       198273.79     1944338.002      198037.264
     1943997.256      197810.364
#Sta/Elev= 30
       0 2145.11    19.5 2142.47    87.9  2137.7     166 2127.87   214.9 2116.43
   234.4 2113.79   283.2 2101.23   302.8 2093.97   312.5 2086.99   341.8 2074.17
   351.6 2068.37   390.6 2045.14   400.4 2037.18   410.2 2025.94   420.2 2021.66
   430.2 2021.19   434.5 2021.62   449.5 2024.06     510  2033.9   569.9 2039.51
   579.9 2041.57   589.9 2045.29   599.9 2052.39   659.8  2077.7   689.8  2088.5
   709.7  2100.8   749.7 2118.02   769.6 2125.15   789.6 2129.26   819.6 2138.91
#Mann= 3 , 0 , 0
       0      .1       0   434.5    .045       0   449.5      .1       0
Bank Sta=434.5,449.5
XS Rating Curve= 0 ,0
Exp/Cntr=0.3,0.1

Type RM Length L Ch R = 1 ,24496.2 ,382.4,386,386.4
XS GIS Cut Line= 3
     1944752.566      198196.292     1944586.963      197734.001
     1944522.603      197344.179
#Sta/Elev= 30
       0 2134.01    58.9 2128.26     108 2122.06   127.7 2120.69   137.5 2118.73
   157.1 2111.69   206.2 2089.15   216.1 2087.72   225.9 2084.74   314.3 2045.71
   324.1 2045.48   373.2 2026.69     383 2024.71   422.3 2021.78   483.6 2013.86
   491.1 2013.75   498.6 2015.42   520.7 2021.11   530.6 2026.34   599.7 2055.83
   609.6 2059.03   619.5 2060.07   639.2 2068.37   698.5 2087.15   708.4 2087.21
     738 2095.98   787.4 2105.27   807.1 2107.01   866.4 2115.69   886.2 2119.51
#Mann= 3 , 0 , 0
       0      .1       0   483.6    .045       0   498.6      .1       0
Bank Sta=483.6,498.6
XS Rating Curve= 0 ,0
Exp/Cntr=0.3,0.1

Type RM Length L Ch R = 1 ,24110   ,405.6,410.8,412.1
XS GIS Cut Line= 3
     1945071.974       198150.61     1944970.672      197750.524
     1944904.728      197345.906
#Sta/Elev= 30
       0 2122.16    19.6 2122.91    29.5 2121.98      59 2115.85    78.6 2113.65
   147.4 2090.05   157.2 2087.22     167 2087.19   245.7 2058.63   255.5 2057.63
   265.3 2055.26   343.9 2026.57   353.8 2024.44   363.6 2023.97   419.2 2009.85
   432.7 2008.45   434.2 2008.57   452.7 2009.48   502.7 2018.59   512.7 2021.32
   532.7 2029.96   542.7 2031.31   552.7  2034.8   632.7 2072.57   652.7 2077.54
   692.7  2096.7   702.7 2100.58   722.7 2104.41   742.7 2105.68   822.7 2114.81
#Mann= 3 , 0 , 0
       0      .1       0   419.2    .045       0   434.2      .1       0
Bank Sta=419.2,434.2
XS Rating Curve= 0 ,0
Exp/Cntr=0.3,0.1

Type RM Length L Ch R = 1 ,23699   ,396.3,380.5,367.7
XS GIS Cut Line= 3
     1945327.117      198078.693     1945352.266      197655.315
     1945323.145       197245.81
#Sta/Elev= 30
       0  2062.3    19.7  2058.9    78.9 2055.88    88.8    2056   108.5 2053.87
   118.4 2052.14   167.7 2039.75   177.5 2039.38   187.4 2037.59   256.4  2021.1
   276.2  2018.9   335.4  2006.7   355.1 2004.16   404.4  2002.4   416.6 2001.29
   431.6 1999.67   433.9 1999.46   453.4 2000.57   463.2 2002.17   482.8 2011.22
   512.1 2023.04   551.2 2041.36     561 2041.77   639.2 2077.71   648.9 2078.56
   678.3 2091.52   707.6 2101.21   727.1 2106.24   746.7 2108.17   834.7  2122.1
#Mann= 3 , 0 , 0
       0      .1       0   416.6    .045       0   431.6      .1       0
Bank Sta=416.6,431.6
XS Rating Curve= 0 ,0
Exp/Cntr=0.3,0.1

Type RM Length L Ch R = 1 ,23318.4 ,370.1,375,380
XS GIS Cut Line= 3
     1946025.443      197832.844     1945701.664      197601.482
     1945420.993      197218.307
#Sta/Elev= 30
       0 2080.53    29.8 2078.04    49.7  2074.9    79.6 2071.51   129.3 2063.09
   149.2 2056.97   179.1 2049.42     199  2045.7   238.8 2032.78   258.7 2024.09
   278.6 2018.18   298.5  2013.3   348.2 2003.05   368.1 2001.55   446.1 1988.91
   457.3 1988.33   461.1 1989.18   467.2 1990.54   477.1  1994.5     487  1996.7
   506.8 2003.97   595.8 2042.71   615.6 2047.57   665.1 2066.65   704.7 2079.93
   714.6 2082.06   724.5 2083.03   754.2 2091.48   823.4 2106.13   872.9 2113.77
#Mann= 3 , 0 , 0
       0      .1       0   446.1    .045       0   461.1      .1       0
Bank Sta=446.1,461.1
XS Rating Curve= 0 ,0
Exp/Cntr=0.3,0.1

Type RM Length L Ch R = 1 ,22943.3 ,347.7,337.8,328
XS GIS Cut Line= 3
     1946117.605      197772.603     1945974.844      197370.708
     1945805.773      196996.741
#Sta/Elev= 30
       0 2089.59    39.7 2086.62    99.2 2083.71     119 2081.24   148.8 2074.81
   168.6 2071.98   188.4 2064.55     248 2037.32   257.9 2036.69   287.6 2022.98
   337.2 2002.17   357.1 1997.97   386.8 1987.59   447.5 1977.82   455.8  1977.5
   462.5  1977.6   475.4 1979.39   494.9 1989.91   504.7 1993.29   563.3  2005.9
   592.6 2016.54   612.2 2022.18   651.2 2028.38   670.8  2029.4   680.6 2031.27
   729.4  2049.3   758.7 2056.58   768.5 2056.46   797.8 2066.34   836.9 2068.93
#Mann= 3 , 0 , 0
       0      .1       0   447.5    .045       0   462.5      .1       0
Bank Sta=447.5,462.5
XS Rating Curve= 0 ,0
Exp/Cntr=0.3,0.1

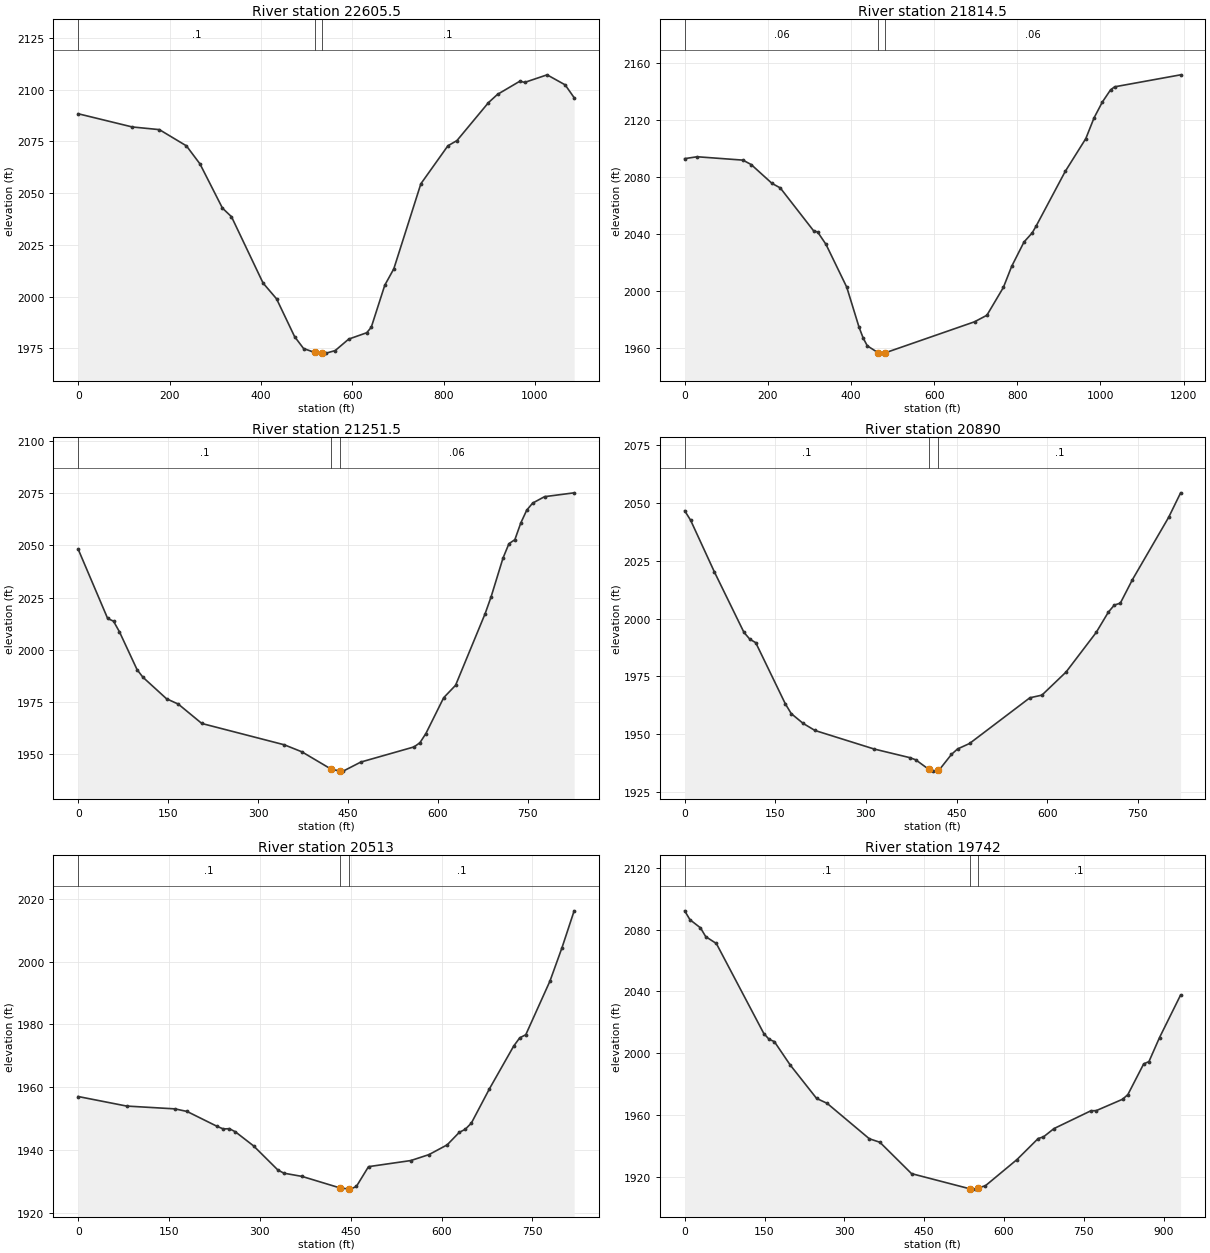
Type RM Length L Ch R = 1 ,22605.5 ,753.5,790.5,827.5
XS GIS Cut Line= 3
     1946370.698      197662.626      1946289.74      197205.835
     1945817.432      196801.261
#Sta/Elev= 30
       0 2088.39   118.4 2082.01   177.7 2080.72   236.9 2072.88   266.5 2064.18
   315.8 2042.78   335.6 2038.62   404.7 2006.57   434.3 1998.92   473.8 1980.65
   493.5 1974.89   517.9 1973.01   532.9 1972.72   542.9 1972.69   562.6 1973.92
   592.2 1979.47   631.7 1982.55   641.6 1985.19   671.2 2005.53     691 2013.46
   750.2 2054.55   809.4 2072.91   829.2 2075.43   898.2 2093.78     918 2097.76
   967.4 2104.19   977.2 2103.53  1026.6 2107.21  1066.1 2102.36  1085.8 2096.16
#Mann= 3 , 0 , 0
       0      .1       0   517.9    .045       0   532.9      .1       0
Bank Sta=517.9,532.9
XS Rating Curve= 0 ,0
Exp/Cntr=0.3,0.1

Type RM Length L Ch R = 1 ,21814.5 ,576.3,562.7,547.8
XS GIS Cut Line= 3
     1946412.394      197654.345       1946528.8      197303.256
      1947104.38      196715.221
#Sta/Elev= 30
       0 2092.99      30 2094.31     140 2091.94     160 2088.82   209.9  2075.6
   229.9 2072.38   309.9 2042.27   319.9 2041.32   339.9 2032.64   389.7  2002.6
   419.4 1974.35   429.4 1966.66   439.3 1961.26   465.6 1956.37   478.9 1956.15
   480.6  1956.2     697 1978.19   726.8 1982.79   766.4 2002.35   786.3 2017.15
     816 2034.31   835.8 2040.77   845.8 2045.86   915.1 2083.95   964.7  2107.1
   984.5 2121.67  1004.4 2132.78  1024.2 2141.38  1034.1 2143.52  1192.7 2151.95
#Mann= 3 , 0 , 0
       0     .06       0   465.6    .045       0   480.6     .06       0
Bank Sta=465.6,480.6
XS Rating Curve= 0 ,0
Exp/Cntr=0.3,0.1

Type RM Length L Ch R = 1 ,21251.5 ,348.6,361.3,375.5
XS GIS Cut Line= 3
     1947020.097      197880.257     1947066.482       197371.68
     1947120.884      197059.848
#Sta/Elev= 30
       0 2048.08    49.1 2014.98    58.9 2013.68    68.8 2008.59    98.2 1990.47
     108 1986.85   147.3 1976.57     167    1974   206.2 1964.74   343.7 1954.55
   373.2 1951.17   422.3 1942.83   437.3 1941.99   441.9 1941.95   471.4 1946.29
   560.2 1953.54     570 1955.55   579.9 1959.94   609.6 1977.08   629.4 1983.01
   678.8 2017.34   688.7 2025.36   708.5 2043.84   718.4 2050.74   728.3 2052.67
   738.2 2060.67   748.1 2066.79     758 2070.18   777.8 2073.24   827.2 2075.08
#Mann= 3 , 0 , 0
       0      .1       0   422.3    .045       0   437.3     .06       0
Bank Sta=422.3,437.3
XS Rating Curve= 0 ,0
Exp/Cntr=0.3,0.1

Type RM Length L Ch R = 1 ,20890   ,385.9,376.7,366.1
XS GIS Cut Line= 3
     1947132.618      197911.848     1947380.679      197583.433
     1947647.672      197273.384
#Sta/Elev= 30
       0 2046.68     9.8 2042.58      49 2020.28      98 1994.04   107.8 1991.05
   117.6 1989.54   166.6 1963.04   176.4  1958.8     196 1954.59   215.6 1951.52
   313.6 1943.48   372.4 1939.76   382.2 1938.83   404.1 1934.66   411.6 1933.91
   419.1  1934.4   421.6 1934.57   441.5 1941.16   451.5  1943.5   471.4 1945.88
   571.2 1965.67   591.2 1966.83   631.1 1976.82     681 1993.98     701 2002.72
     711 2005.84   720.9 2006.65   740.9 2016.81   800.8 2043.79   820.7 2054.44
#Mann= 3 , 0 , 0
       0      .1       0   404.1    .045       0   419.1      .1       0
Bank Sta=404.1,419.1
XS Rating Curve= 0 ,0
Exp/Cntr=0.3,0.1

Type RM Length L Ch R = 1 ,20513   ,786,770.9,755.6
XS GIS Cut Line= 3
     1947590.538        198160.5     1947698.471      197765.469
     1947803.751      197369.736
#Sta/Elev= 30
       0 1957.01    79.9 1953.97   159.8 1953.07   179.8 1952.24   229.7 1947.46
   239.7 1946.66   249.7 1946.75   259.7 1945.73   289.6 1941.26   329.6 1933.59
   339.6 1932.55   369.6 1931.52   431.7 1927.88   446.7 1927.47   449.5 1927.46
   459.4 1928.32   479.4 1934.63   549.3 1936.58   579.3 1938.48   609.3 1941.59
   629.2 1945.56   639.2 1946.57   649.2 1948.52   679.2 1959.51   719.1 1973.09
   729.1 1975.74   739.1 1976.73   779.1 1993.88     799 2004.55     819 2016.27
#Mann= 3 , 0 , 0
       0      .1       0   431.7    .045       0   446.7      .1       0
Bank Sta=431.7,446.7
XS Rating Curve= 0 ,0
Exp/Cntr=0.3,0.1

Type RM Length L Ch R = 1 ,19742   ,459.2,473,487
XS GIS Cut Line= 2
     1948487.193      198161.996     1948123.089      197304.372
#Sta/Elev= 30
       0 2092.08     9.9 2086.36    29.7 2081.08    39.6 2075.38    59.5 2070.99
   148.7 2012.84   158.6 2009.11   168.5 2007.63   198.2 1992.56   247.8 1970.96
   267.6 1967.78   346.9  1944.9   366.7 1942.65   426.2 1922.38   535.4 1912.62
   545.2 1912.38   550.4 1913.05     565 1914.57   624.4 1931.51   664.1 1945.07
     674  1946.1   693.8 1951.48   763.2 1962.98   773.1 1963.05   822.7 1970.42
   832.6 1973.43   862.3 1993.23   872.2 1994.74   892.1 2010.27   931.7 2037.76
#Mann= 3 , 0 , 0
       0      .1       0   535.4    .045       0   550.4      .1       0
Bank Sta=535.4,550.4
XS Rating Curve= 0 ,0
Exp/Cntr=0.3,0.1

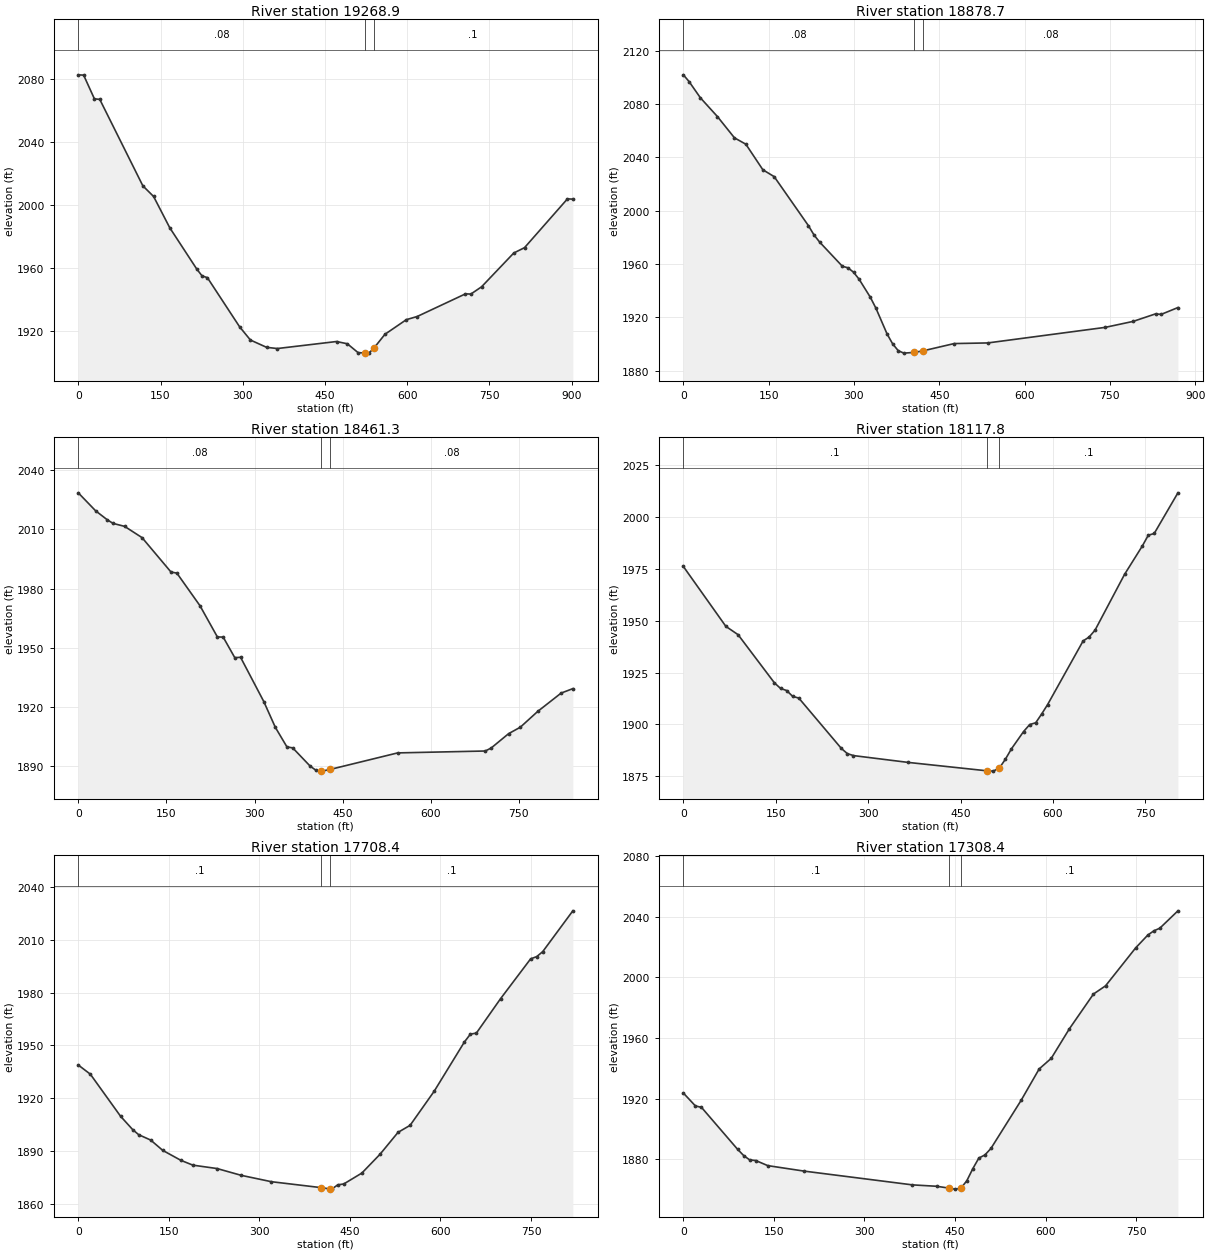
Type RM Length L Ch R = 1 ,19268.9 ,383.4,390.2,396.8
XS GIS Cut Line= 3
     1948628.478      198148.899     1948729.084      197648.613
     1948829.212      197269.915
#Sta/Elev= 30
       0  2082.8     9.8  2082.6    29.4 2067.56    39.2  2067.2   117.8 2012.24
   137.4 2005.47   166.8 1985.64   215.9 1959.46   225.7 1955.03   235.5 1953.88
   294.4 1922.57     314 1914.24   343.5  1909.6   363.1 1908.84     471  1913.3
   490.7 1911.87   510.3 1906.24   523.7 1905.97   529.9 1905.92   538.7  1908.9
   559.3 1917.89   598.4  1927.2     618 1929.18   706.2 1943.59     716 1943.46
   735.5 1948.06   794.3 1969.56   813.9 1972.95   892.2 2003.98     902 2003.78
#Mann= 3 , 0 , 0
       0     .08       0   523.7    .045       0   538.7      .1       0
Bank Sta=523.7,538.7
XS Rating Curve= 0 ,0
Exp/Cntr=0.3,0.1

Type RM Length L Ch R = 1 ,18878.7 ,431,417.4,403.9
XS GIS Cut Line= 3
     1948698.712      198206.567     1948910.282      198039.291
     1949217.305      197523.789
#Sta/Elev= 30
       0 2101.93      10 2096.91      30 2084.68    59.9 2070.64    89.9 2054.67
   109.9 2049.91   139.8 2030.75   159.8 2025.56   219.8 1988.92   229.8 1981.83
   239.7  1976.5   279.6  1958.4   289.4 1957.24   299.2 1953.96     309 1948.71
   328.7 1935.23   338.6 1926.98   358.2 1907.67   368.1 1900.16   377.9 1895.09
   387.7 1893.26   405.9  1893.8   420.9 1894.92   476.3 1900.43   535.3  1900.9
   741.8 1912.57     791 1917.06   830.4  1922.7   840.2  1922.3   869.7 1927.43
#Mann= 3 , 0 , 0
       0     .08       0   405.9    .045       0   420.9     .08       0
Bank Sta=405.9,420.9
XS Rating Curve= 0 ,0
Exp/Cntr=0.3,0.1

Type RM Length L Ch R = 1 ,18461.3 ,338.3,343.4,350.9
XS GIS Cut Line= 3
      1949422.34      198384.982     1949390.833      197981.622
     1949366.716      197544.954
#Sta/Elev= 30
       0 2028.51    29.6 2019.38    49.3 2014.86    59.2 2013.02    78.9  2011.5
   108.6 2005.79   157.9 1988.34   167.8 1987.82   207.2 1971.27   236.8 1955.45
   246.7 1955.36   266.4 1944.96   276.3 1945.12   315.8  1922.7   335.5  1909.6
   355.2 1899.71   365.1 1899.19   394.7 1889.97   404.6 1887.85   413.8 1887.45
   414.5 1887.42   428.8 1888.28   543.7 1896.66   692.8 1897.62   702.8 1899.12
   732.6 1906.42   752.5 1909.69   782.3 1917.74     822 1926.99   841.9 1929.24
#Mann= 3 , 0 , 0
       0     .08       0   413.8    .045       0   428.8     .08       0
Bank Sta=413.8,428.8
XS Rating Curve= 0 ,0
Exp/Cntr=0.3,0.1

Type RM Length L Ch R = 1 ,18117.8 ,402.2,409.3,414.8
XS GIS Cut Line= 3
     1949652.441      198302.691     1949741.897      197737.789
     1949791.596      197512.491
#Sta/Elev= 30
       0 1976.13      69 1947.26    88.8 1943.26   147.9 1920.01   157.8 1917.35
   167.6 1916.35   177.5 1913.51   187.4  1912.7   256.4 1888.45   266.2 1885.93
   276.1 1884.99   364.9  1881.7     493 1877.64   502.9  1877.5   512.8 1878.95
   522.6  1883.2   532.5 1888.25   552.2 1896.57   562.1 1899.94   571.9 1900.81
   581.6 1905.06   591.2 1909.58   648.8 1940.23   658.5 1942.11   668.1  1945.4
   716.1 1972.33     745 1986.04   754.6 1991.19   764.2 1992.02   802.7 2011.62
#Mann= 3 , 0 , 0
       0      .1       0     493    .045       0   512.8      .1       0
Bank Sta=493,512.8
XS Rating Curve= 0 ,0
Exp/Cntr=0.3,0.1

Type RM Length L Ch R = 1 ,17708.4 ,407.7,399.9,391.8
XS GIS Cut Line= 3
     1949892.974      198322.384     1950079.856       197957.59
     1950280.584      197600.737
#Sta/Elev= 30
       0  1938.8      20 1933.59      70 1909.72      90 1902.15     100 1899.22
     120 1896.15     140 1890.28     170 1884.64   189.9  1881.9   229.9 1879.98
   269.9 1876.12   319.9  1872.5   402.4 1869.13   417.4 1868.36   419.9 1868.28
   429.8 1870.71   439.8 1871.21   469.8 1877.41   499.8 1888.06   529.7 1900.53
   549.7 1904.53   589.6  1923.9   639.6 1951.86   649.6 1956.35   659.5 1956.94
   699.5 1976.46   749.4 1999.13   759.4 2000.38   769.4 2003.22   819.3 2026.41
#Mann= 3 , 0 , 0
       0      .1       0   402.4    .045       0   417.4      .1       0
Bank Sta=402.4,417.4
XS Rating Curve= 0 ,0
Exp/Cntr=0.3,0.1

Type RM Length L Ch R = 1 ,17308.4 ,400.7,400,398.7
XS GIS Cut Line= 3
     1950386.711      198527.717     1950438.699      198121.555
     1950500.185       197716.56
#Sta/Elev= 30
       0  1923.7      20 1915.18      30 1914.26    89.9 1886.55    99.9 1882.47
   109.9 1879.58   119.8  1879.2   139.8 1875.82   199.7 1872.22   379.5 1863.12
   419.5  1862.2   439.4 1861.02   449.4 1860.32   459.4 1860.83   469.4  1865.8
   479.4 1873.81   489.4 1880.82   499.4 1882.85   509.4 1887.14   559.3  1918.8
   589.3 1939.58   609.3 1946.58   639.3 1966.04   679.2 1988.98   699.2 1994.38
   749.2 2019.47   769.2 2027.86   779.2 2030.66   789.1  2032.4   819.1 2043.86
#Mann= 3 , 0 , 0
       0      .1       0   439.4    .045       0   459.4      .1       0
Bank Sta=439.4,459.4
XS Rating Curve= 0 ,0
Exp/Cntr=0.3,0.1

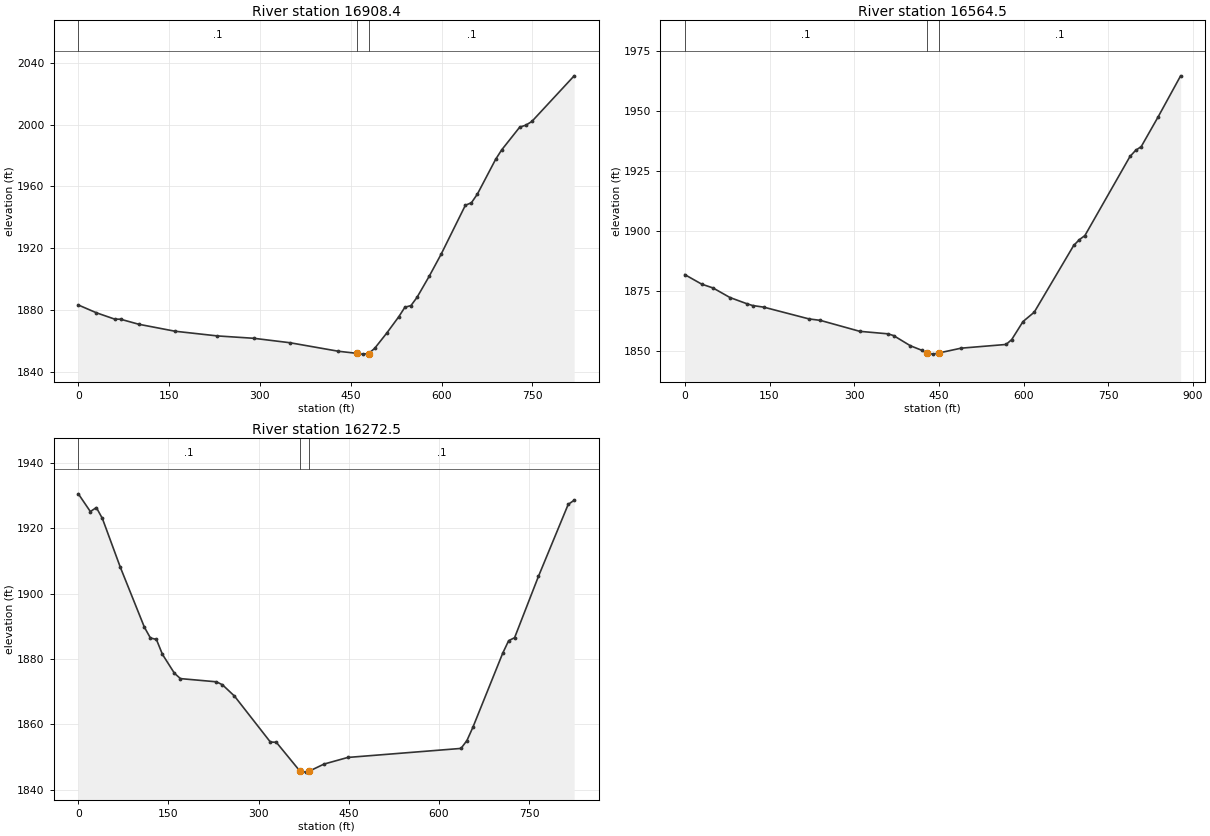
Type RM Length L Ch R = 1 ,16908.4 ,345.7,343.9,342.1
XS GIS Cut Line= 3
     1950796.203      198578.328     1950835.557      198170.627
     1950873.669      197762.984
#Sta/Elev= 30
       0 1883.09      30 1878.02    59.9 1873.96    69.9 1873.86    99.9  1870.6
   159.8 1866.09   229.8 1863.05   289.7 1861.52   349.6 1858.64   429.6 1853.12
   459.5  1851.8   469.5 1851.26   479.5 1851.66   489.5 1855.01   509.4 1864.87
   529.4 1875.53   539.4 1881.63   549.4  1882.7   559.4 1888.01   579.4 1901.59
   599.3 1916.02   639.3 1947.68   649.3 1949.32   659.2 1954.96   689.2 1977.38
   699.2 1983.52   729.1  1998.3   739.1 1999.55   749.1 2001.96     819 2031.53
#Mann= 3 , 0 , 0
       0      .1       0   459.5    .045       0   479.5      .1       0
Bank Sta=459.5,479.5
XS Rating Curve= 0 ,0
Exp/Cntr=0.3,0.1

Type RM Length L Ch R = 1 ,16564.5 ,298.5,291.9,285.4
XS GIS Cut Line= 3
      1951160.42       198643.72     1951168.234      198363.985
     1951181.486      197765.951
#Sta/Elev= 30
       0 1882.01      30 1878.03      50 1876.45      80 1872.46   109.9 1869.88
   119.9 1869.14   139.9 1868.45   219.9 1863.55   239.9 1862.95   309.8 1858.38
   359.6 1857.34   369.6 1856.62   399.5 1852.36   419.4 1850.51   428.7 1849.27
   439.4 1848.88   449.3 1849.33   489.2 1851.36     569 1852.91   578.9 1854.95
   598.9 1862.45   618.8 1866.36   688.6 1894.14   698.6 1896.56   708.5 1898.28
   788.3 1931.22   798.3 1933.78   808.2 1935.33   838.2 1947.74     878 1964.83
#Mann= 3 , 0 , 0
       0      .1       0   428.7    .045       0   449.3      .1       0
Bank Sta=428.7,449.3
XS Rating Curve= 0 ,0
Exp/Cntr=0.3,0.1

Type RM Length L Ch R = 1 ,16272.5 ,572.2,564.1,558.9
XS GIS Cut Line= 3
     1951589.531       198628.78     1951486.394      198358.003
     1951341.699      197842.751
#Sta/Elev= 30
       0 1930.51      20 1925.09      30 1926.31      40 1922.98    69.9 1908.04
   109.9 1889.72   119.9 1886.43   129.9 1885.98   139.9 1881.43   159.9 1875.63
   169.9    1874   229.8 1873.02   239.8 1872.11   259.8 1868.65   319.5  1854.6
   329.4 1854.53     369 1845.64     379  1845.4   384.4 1845.72   408.7 1847.86
   448.3 1849.89   636.6 1852.65   646.5 1855.06   656.4 1859.11     706 1881.75
   715.9  1885.6   725.8 1886.51   765.5 1905.27     815 1927.28   824.9 1928.55
#Mann= 3 , 0 , 0
       0      .1       0     369    .045       0   384.4      .1       0
Bank Sta=369,384.4
XS Rating Curve= 0 ,0
Exp/Cntr=0.3,0.1