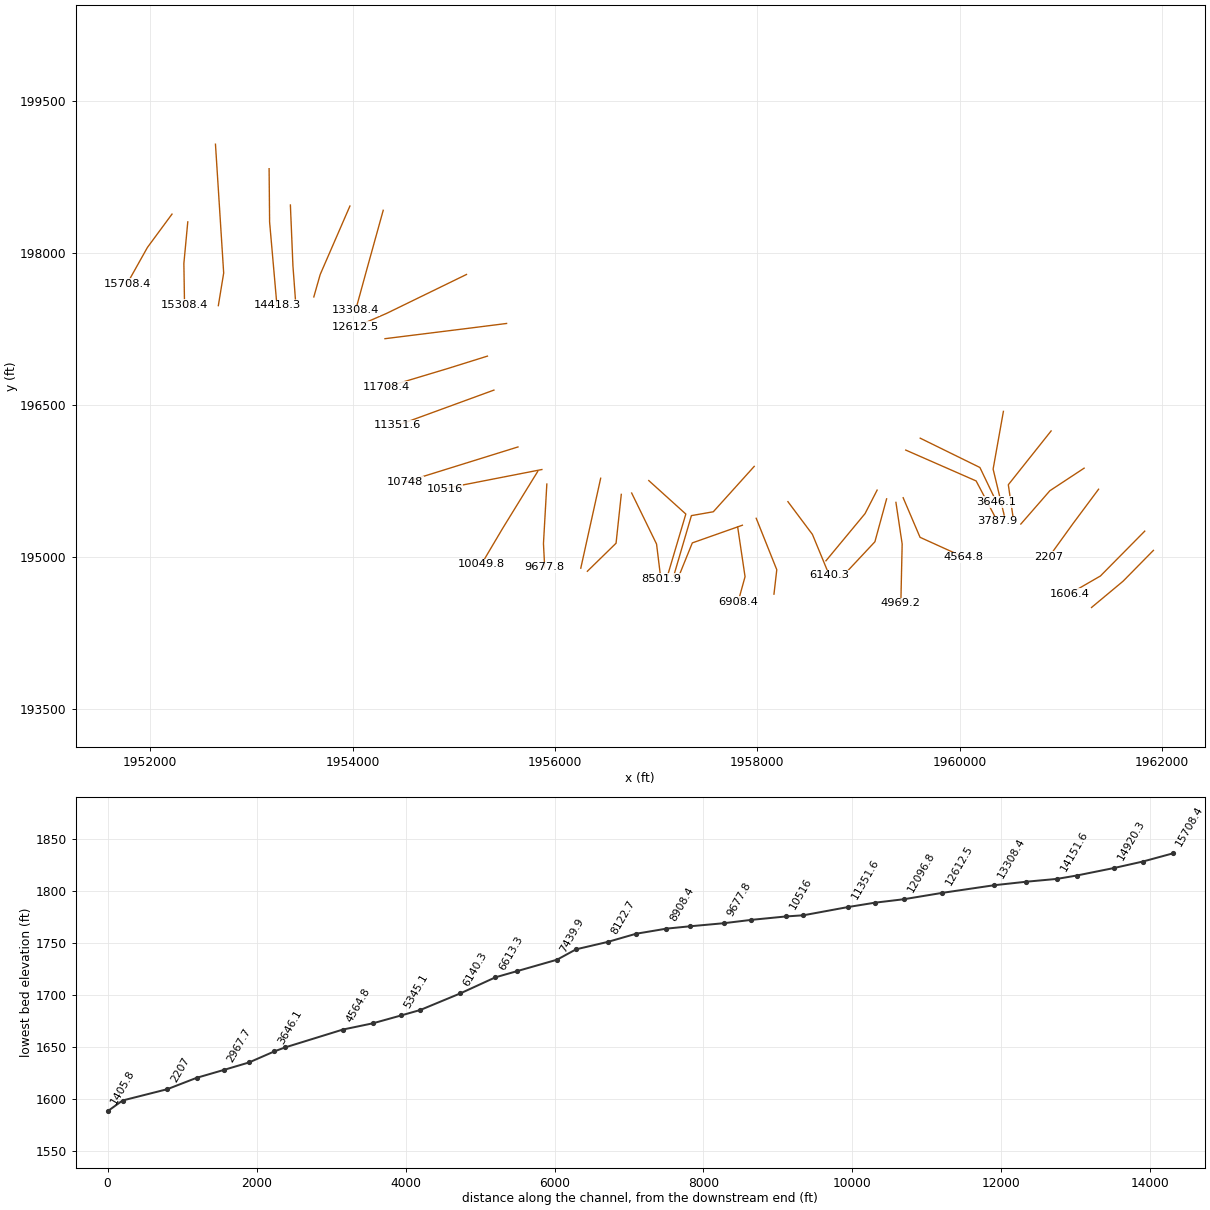
HEC-RAS study MntnCrk.prj: MntnCrk

--- MntnCrk.g01 (geometry) --- (continued)

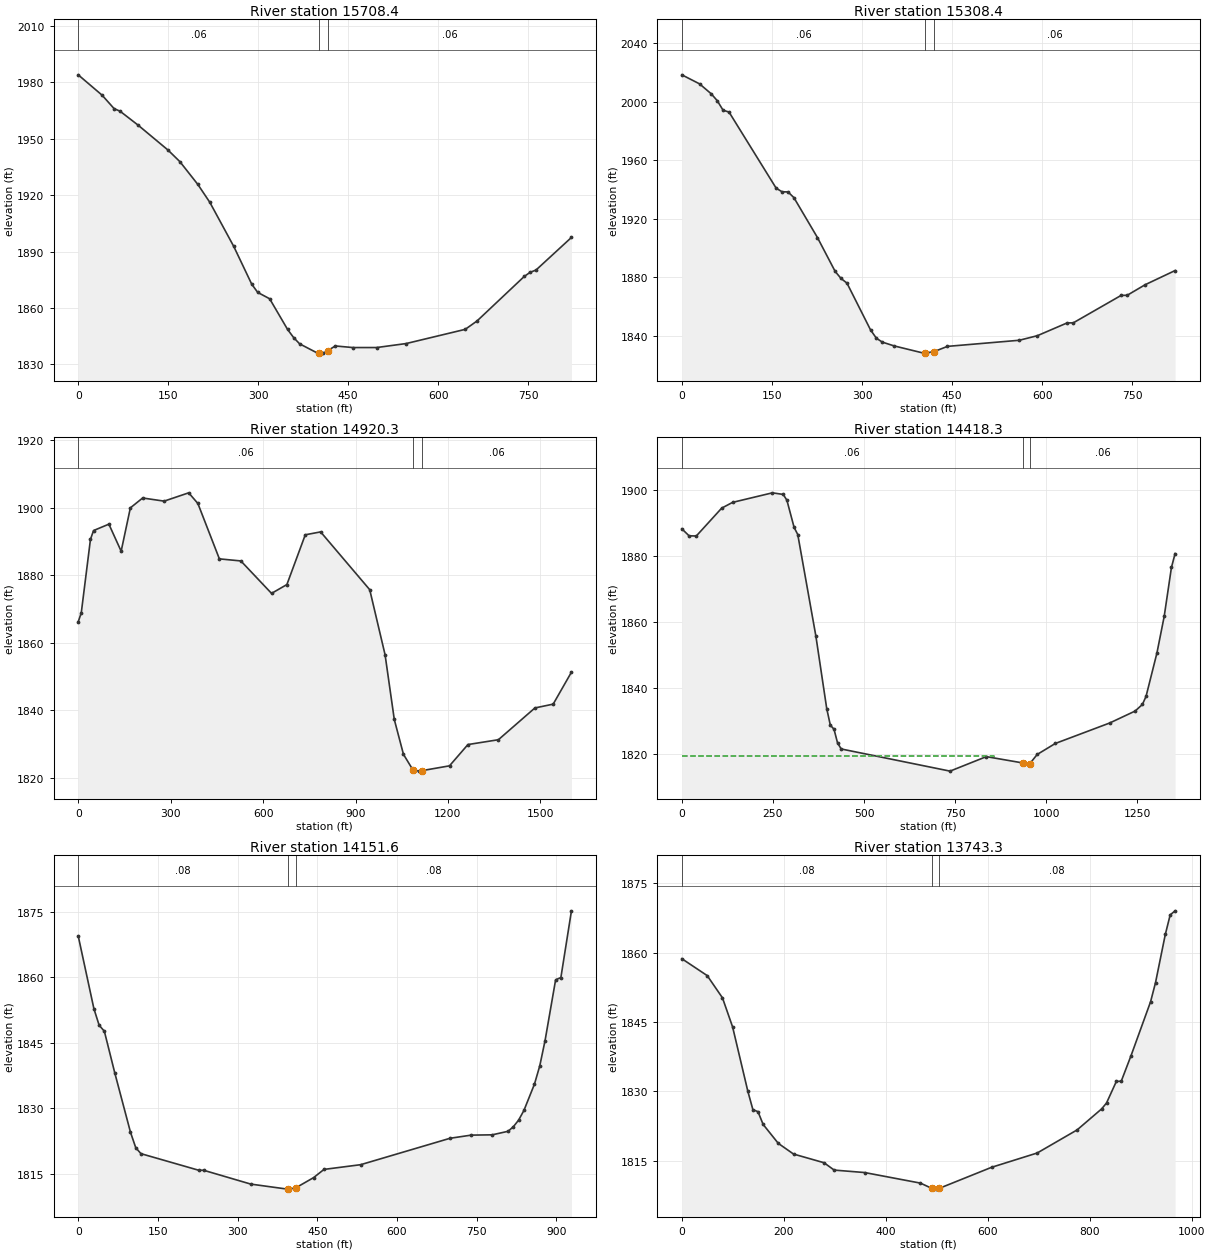
Type RM Length L Ch R = 1 ,15708.4 ,387.7,400,411.9
XS GIS Cut Line= 3
     1952214.682       198386.12      1951971.89      198057.175
     1951769.828      197696.724
#Sta/Elev= 30
       0 1983.93    39.9 1973.09    59.8 1965.98    69.8 1964.59    99.7 1957.22
   149.6 1943.97   169.5 1937.78   199.4 1925.68   219.4 1916.16   259.3 1892.71
   289.2 1872.68   299.2  1868.3   319.1 1864.92     349  1848.6     359 1844.32
     369 1840.98   398.9 1836.03   401.3 1836.03   408.8 1836.05   416.3 1837.42
   428.5 1839.84     458 1838.99   497.4    1839   546.6 1841.12     645 1848.66
   664.6 1853.08   743.4 1876.77   753.2 1878.97     763 1880.18   822.1 1897.51
#Mann= 3 , 0 , 0
       0     .06       0   401.3    .045       0   416.3     .06       0
Bank Sta=401.3,416.3
XS Rating Curve= 0 ,0
Exp/Cntr=0.3,0.1

Type RM Length L Ch R = 1 ,15308.4 ,384.5,388.1,389.3
XS GIS Cut Line= 3
     1952370.712       198309.54     1952332.028      197898.941
     1952338.519      197490.007
#Sta/Elev= 30
       0 2018.37    29.5  2012.2    49.1 2005.35    58.9 2000.73    68.7 1994.19
    78.6 1992.93   157.1 1940.92   166.9 1938.46   176.8 1938.38   186.6 1934.49
   225.8 1907.23   255.3 1884.09   265.1 1879.26     275 1876.07   314.2 1844.16
     324 1838.41   333.9 1835.77   353.5 1833.18   402.6 1828.25   404.9 1828.26
   419.9 1829.26   442.3 1832.86     562 1837.04     592 1840.15   641.8 1848.92
   651.8 1848.92   731.6  1867.7   741.6 1867.75   771.5 1874.97   821.4 1884.66
#Mann= 3 , 0 , 0
       0     .06       0   404.9    .045       0   419.9     .06       0
Bank Sta=404.9,419.9
XS Rating Curve= 0 ,0
Exp/Cntr=0.3,0.1

Type RM Length L Ch R = 1 ,14920.3 ,502,502.1,502.2
XS GIS Cut Line= 3
     1952644.268      199076.325     1952725.441      197804.053
     1952672.647      197482.319
#Sta/Elev= 30
       0  1866.2      10 1868.91    39.8 1890.65    49.8 1893.26    99.6 1895.15
   139.4 1887.14   169.3 1899.98   209.2  1902.9   278.9 1901.97   358.6 1904.43
   388.4 1901.28   458.2 1884.87   527.9 1884.26   627.5 1874.65   677.3 1877.26
     737    1892   786.8 1892.86   946.2 1875.74     996 1856.47  1025.9  1837.3
  1055.7 1826.98  1085.6 1822.48  1105.5 1822.01  1115.5 1822.15  1205.1 1823.58
  1264.9 1829.88  1363.8 1831.31  1482.3 1840.72  1541.6 1841.85  1600.9 1851.32
#Mann= 3 , 0 , 0
       0     .06       0  1085.6    .045       0  1115.5     .06       0
Bank Sta=1085.6,1115.5
XS Rating Curve= 0 ,0
Exp/Cntr=0.3,0.1

Type RM Length L Ch R = 1 ,14418.3 ,268.2,266.1,262.3
XS GIS Cut Line= 3
     1953174.381      198834.461     1953179.351      198307.661
      1953251.82       197484.21
#Sta/Elev= 30
       0 1888.29    19.9 1886.16    39.8 1886.12   109.3 1894.56   139.2 1896.31
   248.5 1899.21   278.3 1898.72   288.3 1896.96   308.1 1888.71   318.1 1886.56
   367.8 1855.76   397.6 1833.74   407.5  1828.7   417.5  1827.5   427.4 1823.29
   437.4 1821.49     736 1814.77   835.6 1819.17   935.2 1817.26   955.1 1817.06
     975 1819.82  1024.8 1823.16  1174.2 1829.38  1243.9    1833  1263.8    1835
  1273.8 1837.44  1303.7 1850.62  1323.6  1861.7  1343.5 1876.56  1353.5 1880.77
#Mann= 3 , 0 , 0
       0     .06       0   935.2    .045       0   955.1     .06       0
#XS Ineff= 2 , 0
          855.51 1819.23
Permanent Ineff=
       F       F
Bank Sta=935.2,955.1
XS Rating Curve= 0 ,0
Exp/Cntr=0.3,0.1

Type RM Length L Ch R = 1 ,14151.6 ,417,408.2,401
XS GIS Cut Line= 3
     1953384.764      198476.042     1953409.895      197876.116
     1953434.192      197549.212
#Sta/Elev= 30
       0 1869.45    29.5 1852.82    39.4 1849.01    49.2 1847.65    68.9 1838.08
    98.4 1824.54   108.3    1821   118.1 1819.64   226.4 1815.86   236.2 1815.84
   324.8 1812.68   393.7 1811.53   394.1 1811.53   409.1  1811.8     443 1814.16
   462.6 1816.04   531.6 1817.12   699.8 1823.16   739.5 1823.88   779.2 1823.95
   809.1 1824.76     819 1825.81   828.9 1827.32   838.9 1829.54   858.7 1835.55
   868.7 1839.74   878.6 1845.49   898.5  1859.4   908.4 1859.92   928.3 1875.18
#Mann= 3 , 0 , 0
       0     .08       0   394.1    .045       0   409.1     .08       0
Bank Sta=394.1,409.1
XS Rating Curve= 0 ,0
Exp/Cntr=0.3,0.1

Type RM Length L Ch R = 1 ,13743.3 ,431.3,434.9,438.6
XS GIS Cut Line= 3
     1953973.141      198465.867     1953679.369      197789.972
     1953616.337      197568.198
#Sta/Elev= 30
       0 1858.71    49.8 1855.05    79.7 1850.24    99.6 1843.94   129.5 1830.01
   139.4 1826.04   149.4 1825.61   159.4 1822.86   189.2 1818.75   219.1 1816.44
   278.9 1814.56   298.8 1812.97   358.5 1812.44   468.1 1810.15   490.2 1809.02
     498 1808.85   505.2 1809.03   607.5 1813.57   697.1 1816.67   775.4 1821.67
   823.4 1826.21     833 1827.48   852.3 1832.16   861.9  1832.2   881.1 1837.73
   919.5 1849.42   929.1 1853.52   948.3 1863.95   957.9 1868.19   967.5 1869.07
#Mann= 3 , 0 , 0
       0     .08       0   490.2    .045       0   505.2     .08       0
Bank Sta=490.2,505.2
XS Rating Curve= 0 ,0
Exp/Cntr=0.3,0.1

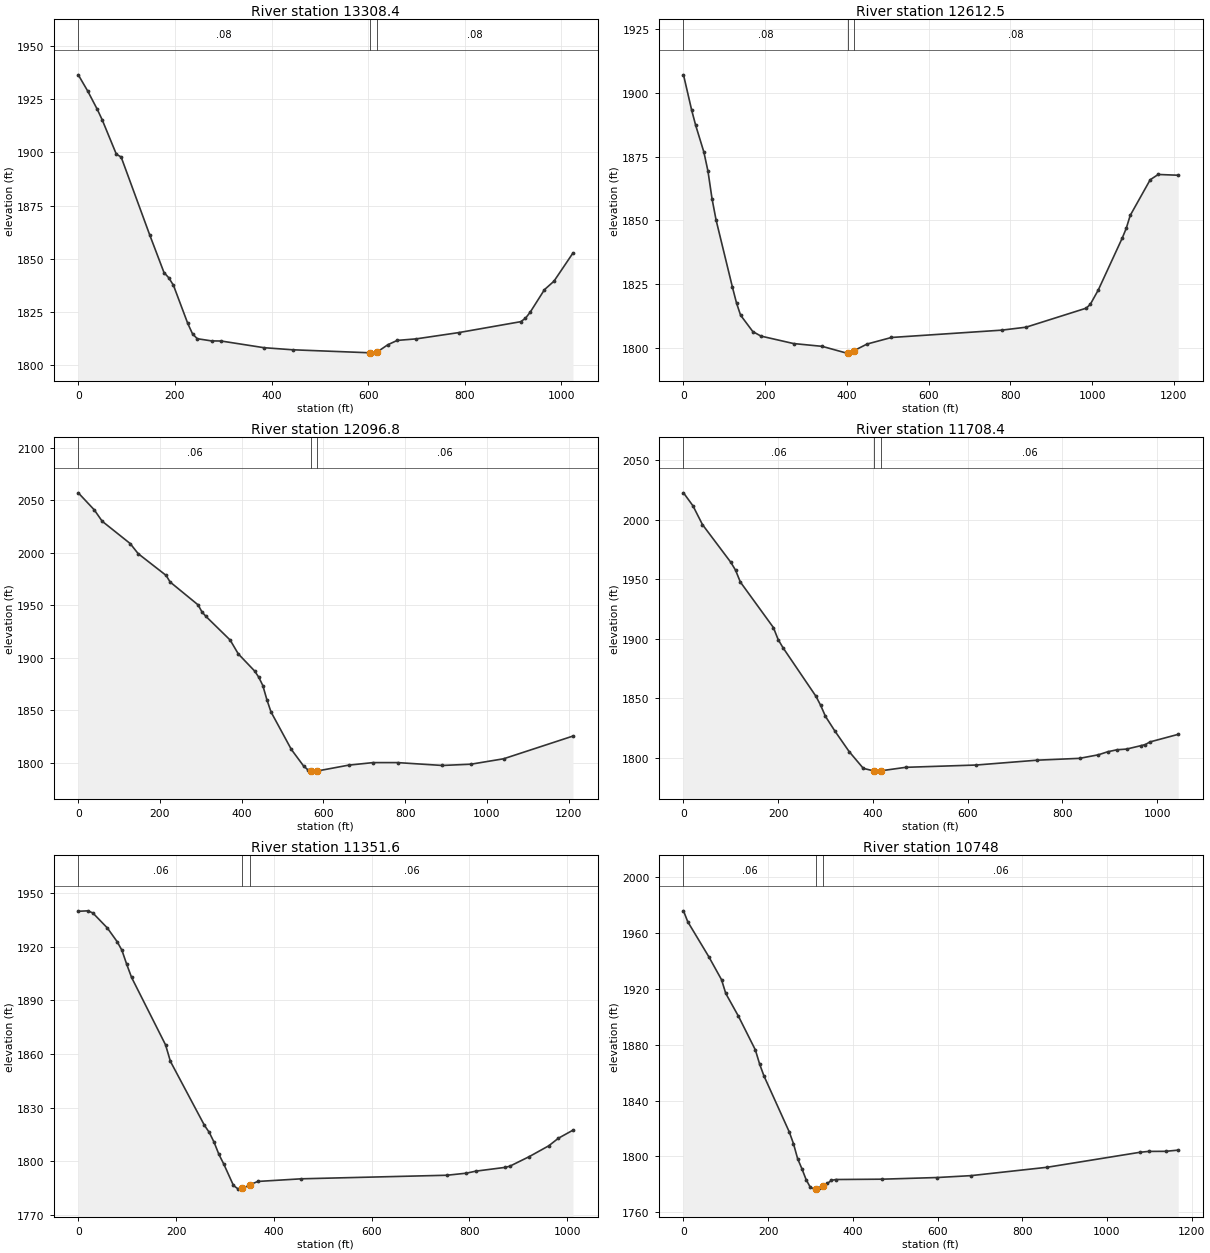
Type RM Length L Ch R = 1 ,13308.4 ,714.7,695.5,676.2
XS GIS Cut Line= 3
     1954302.253      198423.899     1954138.746      197835.318
     1954029.485      197437.085
#Sta/Elev= 30
       0 1936.58    19.7 1928.87    39.4 1920.28    49.3 1915.49    78.8 1899.17
    88.7 1897.86   147.8 1861.18   177.4 1843.42   187.2 1840.98     197 1837.39
   226.6 1819.43   236.5 1814.51   246.3 1812.24   275.9 1811.21   295.6 1811.16
   384.3 1808.01   443.4 1807.03   603.4 1805.61   610.9 1805.45   618.4 1805.95
   640.4 1809.37     660 1811.44   699.4 1812.17   787.8 1815.14   915.7 1820.27
   925.5 1821.89   935.3 1824.75   964.8 1835.36   984.5 1839.35  1023.8 1852.63
#Mann= 3 , 0 , 0
       0     .08       0   603.4    .045       0   618.4     .08       0
Bank Sta=603.4,618.4
XS Rating Curve= 0 ,0
Exp/Cntr=0.3,0.1

Type RM Length L Ch R = 1 ,12612.5 ,521.9,515.5,509.1
XS GIS Cut Line= 3
     1955125.127      197790.131     1954335.385       197405.64
     1954030.569      197273.112
#Sta/Elev= 30
       0 1906.94      20 1893.12    29.9 1887.15    49.9 1876.72    59.9 1869.27
    69.9 1858.44    79.8 1850.13   119.8 1823.88   129.8  1817.7   139.7 1812.96
   169.7 1806.54   189.6 1804.78   269.5 1801.86   339.4 1800.77   399.3 1798.12
   402.8 1798.24   417.8 1799.12   449.2 1801.67     509 1804.24   778.6  1807.1
   838.4 1808.26   985.9 1815.71   995.7 1817.21  1015.2  1822.8  1073.9 1843.13
  1083.7 1846.93  1093.4 1851.98  1142.3 1865.92  1161.9 1867.98  1210.8 1867.68
#Mann= 3 , 0 , 0
       0     .08       0   402.8    .045       0   417.8     .08       0
Bank Sta=402.8,417.8
XS Rating Curve= 0 ,0
Exp/Cntr=0.3,0.1

Type RM Length L Ch R = 1 ,12096.8 ,385.7,388.8,391.7
XS GIS Cut Line= 3
     1955521.513      197306.244     1955172.522      197262.068
     1954319.923      197156.045
#Sta/Elev= 30
       0 2057.14    39.1 2040.92    58.6 2030.04     127 2008.84   146.6 1999.19
     215 1978.47   224.8 1972.19   293.2 1950.41   302.9 1943.59   312.7 1939.35
   371.8 1916.86   391.7 1903.68   431.7 1887.38   441.7 1881.54   451.7 1873.58
   461.7 1860.03   471.7 1848.45   521.6 1812.64   551.6 1796.87   561.6 1793.42
   569.4 1792.53   581.6 1792.01   584.4  1792.1   661.5 1797.69   721.4 1800.13
   781.4 1800.14   891.2  1797.4   961.2 1798.61  1041.1 1803.77  1210.9 1825.42
#Mann= 3 , 0 , 0
       0     .06       0   569.4    .045       0   584.4     .06       0
Bank Sta=569.4,584.4
XS Rating Curve= 0 ,0
Exp/Cntr=0.3,0.1

Type RM Length L Ch R = 1 ,11708.4 ,355.7,356.8,358.1
XS GIS Cut Line= 3
     1955331.979      196983.717     1954940.986      196861.596
     1954333.176      196678.943
#Sta/Elev= 30
       0 2022.68      20 2011.73      40 1995.99    99.9 1964.25   109.9 1957.65
   119.9 1947.75   189.8  1909.4   199.8 1899.31   209.8  1892.6   279.7 1851.55
   289.7 1843.88   299.7 1834.71   319.7 1822.33   349.7 1805.11   379.6 1791.01
   402.1 1788.81   409.6 1788.68   417.1 1788.98   469.1 1791.88   617.9 1793.81
   746.8 1797.89     836 1799.43   875.7  1802.4   895.5 1804.96   915.4 1806.66
   935.2 1807.21     965 1810.03   974.9 1811.02   984.8 1813.24  1044.3 1819.61
#Mann= 3 , 0 , 0
       0     .06       0   402.1    .045       0   417.1     .06       0
Bank Sta=402.1,417.1
XS Rating Curve= 0 ,0
Exp/Cntr=0.3,0.1

Type RM Length L Ch R = 1 ,11351.6 ,604.7,603.6,602.4
XS GIS Cut Line= 2
     1955396.461      196648.354     1954445.825      196301.237
#Sta/Elev= 30
       0 1939.85    19.8  1940.1    29.8  1938.9    59.5 1930.51    79.4 1922.91
    89.3 1918.05    99.2 1910.13   109.1 1902.84   178.6 1865.16   188.5 1855.95
     258 1820.25   267.9 1816.28   277.8 1810.77   287.7 1803.98   297.7 1798.52
   317.5 1786.58   327.4 1784.55   335.9 1784.98   350.9 1786.95   367.1 1788.84
   456.4 1790.32   754.1 1792.31   793.8 1793.46   813.6 1794.61   873.1  1796.7
     883 1797.39   922.7 1802.74   962.4 1808.76   982.3 1813.02    1012  1817.5
#Mann= 3 , 0 , 0
       0     .06       0   335.9    .045       0   350.9     .06       0
Bank Sta=335.9,350.9
XS Rating Curve= 0 ,0
Exp/Cntr=0.3,0.1

Type RM Length L Ch R = 1 ,10748   ,234.2,232,229.7
XS GIS Cut Line= 2
     1955634.162      196086.983     1954518.716      195740.201
#Sta/Elev= 30
       0 1975.85      10 1968.06    59.9 1942.91    89.8 1926.54    99.8  1916.7
   129.8 1900.35   169.7 1876.25   179.7 1866.19   189.7 1857.84   249.6 1817.64
   259.6 1809.22   269.6 1798.28   279.6 1791.18   289.5 1783.42   299.5 1777.84
   309.5 1776.58   313.4  1776.9   319.5 1777.41   328.4 1778.91   339.4 1780.62
   349.4 1782.85   359.4 1783.46   469.2  1783.7     599 1784.89   678.9 1786.24
   858.6 1792.23  1078.2 1802.98  1098.2 1803.59  1138.2 1803.64  1168.1 1804.51
#Mann= 3 , 0 , 0
       0     .06       0   313.4    .045       0   328.4     .06       0
Bank Sta=313.4,328.4
XS Rating Curve= 0 ,0
Exp/Cntr=0.3,0.1

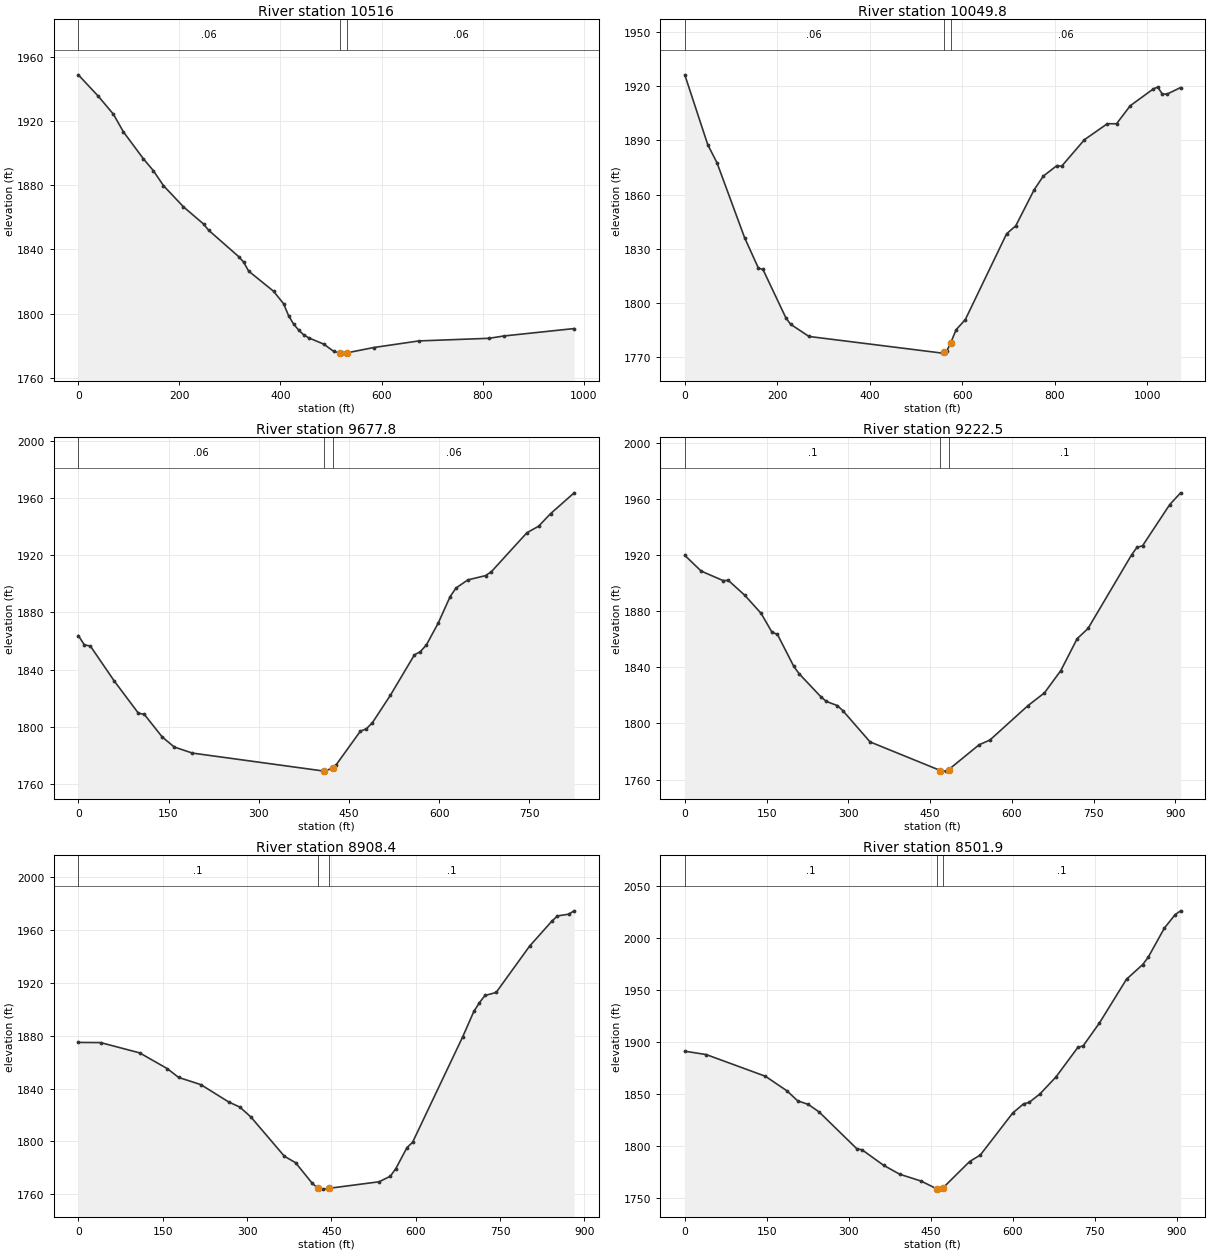
Type RM Length L Ch R = 1 ,10516   ,447.3,466.2,485
XS GIS Cut Line= 2
     1955870.505      195863.894     1954907.465      195676.145
#Sta/Elev= 30
       0 1948.74    39.6 1935.39    69.4 1924.24    89.2 1913.24   128.8 1896.46
   148.7 1888.97   168.5 1879.75   208.1 1866.54   247.8 1855.86   257.7 1852.03
   317.2  1835.6   327.1 1832.17     337 1826.55   386.5 1813.96   406.3 1806.17
   416.2  1798.7   426.2 1793.46   436.1  1789.8     446 1786.86   455.9 1784.99
   485.6 1781.09   505.4 1776.58     517 1775.61   525.3 1775.47     532 1775.68
   584.7 1778.97   673.9 1783.07   812.7  1784.7   842.4 1786.16   981.2 1790.77
#Mann= 3 , 0 , 0
       0     .06       0     517    .045       0     532     .06       0
Bank Sta=517,532
XS Rating Curve= 0 ,0
Exp/Cntr=0.3,0.1

Type RM Length L Ch R = 1 ,10049.8 ,360.1,371.8,383.4
XS GIS Cut Line= 3
     1955828.537      195844.014     1955483.964      195285.187
     1955271.918       194927.36
#Sta/Elev= 30
       0 1926.26    49.7 1887.55    69.6  1877.6   129.3 1836.14   159.2 1819.24
   169.1  1818.5   218.8 1791.63   228.8 1788.18   268.6 1781.41     557 1772.18
   559.9 1772.56     567  1773.5   574.9 1777.71   586.9 1785.14   606.8 1790.76
   696.1 1838.26   715.9 1842.68   755.6 1862.58   775.4 1870.19   805.1 1876.05
     815 1875.63   864.5 1890.35     914  1899.2   933.8 1899.16   963.5 1909.14
    1013 1918.38  1022.9  1919.5  1032.8 1915.67  1042.8 1915.55  1072.5 1919.21
#Mann= 3 , 0 , 0
       0     .06       0   559.9    .045       0   574.9     .06       0
Bank Sta=559.9,574.9
XS Rating Curve= 0 ,0
Exp/Cntr=0.3,0.1

Type RM Length L Ch R = 1 ,9677.8  ,458.9,455.3,451.7
XS GIS Cut Line= 3
     1955919.308      195720.638     1955885.966      195132.779
     1955898.081      194897.314
#Sta/Elev= 30
       0 1863.78      10 1857.28      20 1856.46    59.9  1831.9    99.8 1809.52
   109.8 1808.62   139.7 1792.74   159.7  1785.8   189.6 1781.58   407.8 1769.02
   409.2 1768.95   422.8 1771.05   429.1 1773.54     469 1796.88     479 1798.56
     489 1802.79     519 1822.03   558.9 1850.27   568.8 1852.53   578.8 1857.21
   598.6 1872.58   618.3 1890.99   628.1 1897.05   647.8 1902.72   677.2  1905.7
     687 1908.49     746 1935.69   765.6  1940.3   785.3 1949.03   824.6 1963.62
#Mann= 3 , 0 , 0
       0     .06       0   407.8    .045       0   422.8     .06       0
Bank Sta=407.8,422.8
XS Rating Curve= 0 ,0
Exp/Cntr=0.3,0.1

Type RM Length L Ch R = 1 ,9222.5  ,307.4,314.1,300.9
XS GIS Cut Line= 2
      1956451.42       195777.75     1956254.837       194889.81
#Sta/Elev= 30
       0 1920.02      30 1908.77      70 1902.02      80 1902.06   109.9 1891.55
   139.9 1878.62   159.9 1865.13   169.9 1863.58   199.9 1840.76   209.9 1835.39
   249.8 1818.98   259.8  1815.7   279.8 1812.77   289.8 1809.18   339.8 1786.85
   468.9  1766.4   479.7 1765.99   483.9 1767.05   539.7 1784.78   559.7 1788.21
   629.6 1812.81   659.6 1821.82   689.6 1837.73   719.6 1860.49   739.6 1867.82
   819.5 1920.37   829.5 1925.78   839.5 1926.79   889.4 1956.21   909.4 1964.61
#Mann= 3 , 0 , 0
       0      .1       0   468.9    .045       0   483.9      .1       0
Bank Sta=468.9,483.9
XS Rating Curve= 0 ,0
Exp/Cntr=0.3,0.1

Type RM Length L Ch R = 1 ,8908.4  ,398,406.6,434.9
XS GIS Cut Line= 3
     1956655.172      195618.835     1956603.462      195136.218
     1956319.798      194859.309
#Sta/Elev= 30
       0 1874.94    39.6 1874.81     109 1867.02   158.5    1855   178.3 1848.41
   217.9 1842.95   267.4 1829.81   287.3 1825.92   307.1 1818.32   366.5 1788.65
   386.3 1783.81     416 1768.18   425.9 1764.48   435.8 1763.74   445.8 1764.36
   534.9 1769.32   554.8  1773.5   564.7 1779.33   584.5 1795.24   594.4 1799.22
   683.6 1879.22   703.4 1898.41   713.3 1905.05   723.2 1910.53     743 1912.78
   802.5  1947.9   842.2 1966.88   852.1 1970.81   871.9 1972.13   881.8 1974.68
#Mann= 3 , 0 , 0
       0      .1       0   425.9    .045       0   445.8      .1       0
Bank Sta=425.9,445.8
XS Rating Curve= 0 ,0
Exp/Cntr=0.3,0.1

Type RM Length L Ch R = 1 ,8501.9  ,370.4,379.1,387.8
XS GIS Cut Line= 3
     1956757.663      195631.979     1957003.622      195128.361
     1957046.034      194784.202
#Sta/Elev= 30
       0 1891.14    39.3 1887.88   147.5 1867.09   186.8 1853.16   206.5 1843.55
   226.2 1840.02   245.8 1832.84   314.6 1797.65   324.5 1796.51   363.8 1781.68
   393.3 1773.12   432.6 1766.52   462.1 1758.84     472 1759.84   521.1 1785.28
   540.8 1791.59   600.1 1831.92   619.9 1840.68   629.8 1841.97   649.6 1850.05
   679.4 1866.58     719 1894.69   728.9 1896.27   758.6 1918.17   808.2 1960.19
   837.9 1974.27   847.8 1981.17   877.5 2009.22   897.3 2022.18   907.2 2025.76
#Mann= 3 , 0 , 0
       0      .1       0   462.1    .045       0     472      .1       0
Bank Sta=462.1,472
XS Rating Curve= 0 ,0
Exp/Cntr=0.3,0.1

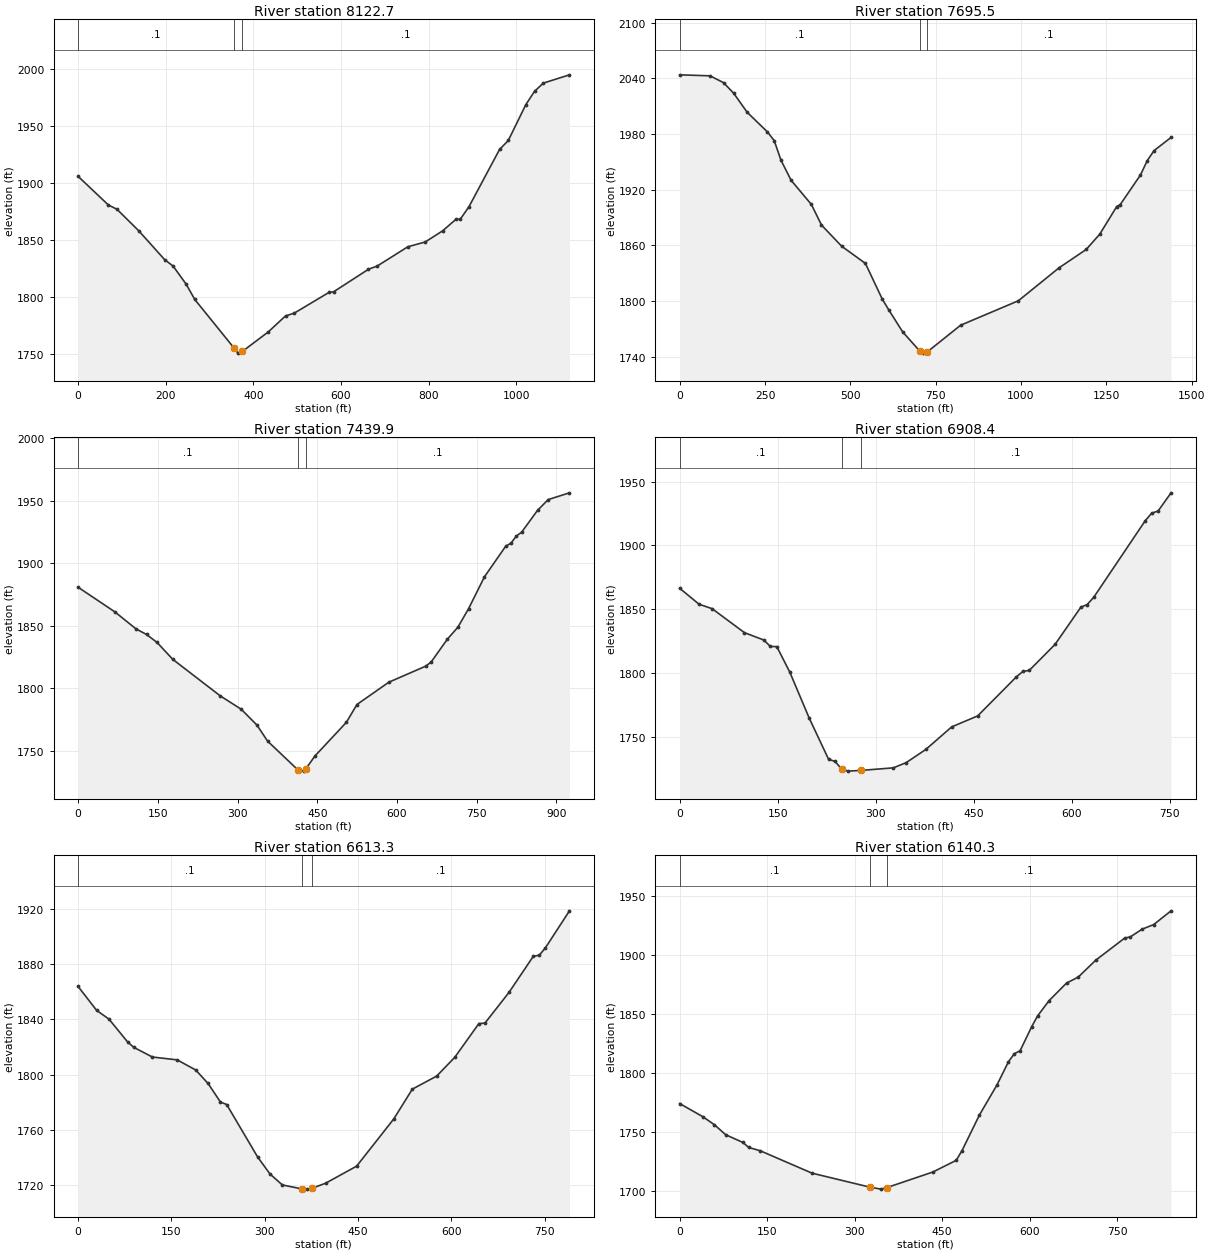
Type RM Length L Ch R = 1 ,8122.7  ,478.4,426.8,375.1
XS GIS Cut Line= 3
     1956926.932      195754.766     1957292.975      195424.341
     1957114.119      194822.039
#Sta/Elev= 30
       0 1905.91      69 1880.85    88.8 1877.02   138.1 1858.33   197.2 1833.05
     217  1827.2   246.6 1811.42   266.3 1798.01     356 1755.43   364.9 1751.02
   374.8 1752.48     434 1769.62   473.4 1783.64   493.1 1786.02   572.9  1804.3
   582.9  1804.7   662.7 1824.52   682.6 1827.31   752.4 1844.19   792.3 1848.42
   832.2 1858.24   862.1 1868.23   872.1 1868.32     892  1879.3   961.8 1929.44
   981.8 1937.35  1021.7 1968.69  1041.6 1980.37  1061.6 1987.58  1121.4 1994.86
#Mann= 3 , 0 , 0
       0      .1       0     356    .045       0   374.8      .1       0
Bank Sta=356,374.8
XS Rating Curve= 0 ,0
Exp/Cntr=0.3,0.1

Type RM Length L Ch R = 1 ,7695.5  ,252.1,255.7,259.2
XS GIS Cut Line= 4
      1957968.87      195894.817     1957564.589      195446.825
     1957348.195       195408.88     1957174.384      194817.419
#Sta/Elev= 30
       0 2043.78      89 2042.71   128.6 2035.29   158.3 2023.92   197.8  2003.4
   257.2 1982.21     277 1972.86   296.8 1951.78   326.4 1930.17   385.8 1904.14
   415.5 1881.89   474.8 1859.03   544.1 1840.59   593.6 1802.06   613.4    1790
   653.4 1766.72   703.3 1746.16   713.3 1743.88   724.3 1744.86   823.1 1773.95
   992.2 1800.28  1111.5 1835.82    1191 1855.59  1230.8 1872.09  1280.5 1901.86
  1290.5 1903.82  1350.1 1935.89    1370  1951.4  1389.9 1962.15  1439.6 1976.31
#Mann= 3 , 0 , 0
       0      .1       0   703.3    .045       0   724.3      .1       0
Bank Sta=703.3,724.3
XS Rating Curve= 0 ,0
Exp/Cntr=0.3,0.1

Type RM Length L Ch R = 1 ,7439.9  ,498.3,531.5,564.5
XS GIS Cut Line= 3
     1957851.803      195313.901     1957357.031      195139.405
     1957207.104      194768.714
#Sta/Elev= 30
       0 1880.94    69.3  1861.2   108.9 1847.64   128.7  1843.2   148.5  1836.8
   178.2 1823.26   267.3 1794.12   306.9 1783.38   336.6 1770.66   356.4 1757.94
   413.6 1734.87   425.6  1733.9   428.6 1735.76   445.4 1745.93   504.8 1772.95
   524.6 1787.17   584.6    1805   654.6 1817.94   664.6 1821.36   694.6 1839.33
   714.6 1849.02   734.6 1863.76   764.6 1889.32   804.6  1913.8   814.5 1916.16
   824.5 1921.87   834.5 1924.98   864.5 1942.48   884.5 1951.04   924.5 1956.44
#Mann= 3 , 0 , 0
       0      .1       0   413.6    .045       0   428.6      .1       0
Bank Sta=413.6,428.6
XS Rating Curve= 0 ,0
Exp/Cntr=0.3,0.1

Type RM Length L Ch R = 1 ,6908.4  ,290.3,295.4,300.6
XS GIS Cut Line= 3
     1957805.418      195296.231     1957878.309      194805.876
     1957810.144      194558.699
#Sta/Elev= 30
       0  1866.4    29.7 1853.85    49.6 1850.41    99.2 1831.57   128.9 1825.79
   138.8 1820.77   148.7 1820.65   168.6  1800.6   198.3 1764.58     228 1732.24
     238 1730.65   247.9 1724.53   257.8 1723.02   277.6 1723.58   327.2  1725.6
     347 1729.76   376.8 1740.02   416.4 1757.71   456.1 1766.28   515.5 1796.96
   525.3 1801.13   535.2 1802.02   574.6 1822.36   614.1 1851.51   623.9 1853.64
   633.8 1859.28   712.7 1919.35   722.6 1925.26   732.4 1926.96   752.2 1941.21
#Mann= 3 , 0 , 0
       0      .1       0   247.9    .045       0   277.6      .1       0
Bank Sta=247.9,277.6
XS Rating Curve= 0 ,0
Exp/Cntr=0.3,0.1

Type RM Length L Ch R = 1 ,6613.3  ,466.7,472.5,478.3
XS GIS Cut Line= 3
     1957988.749      195382.374     1958191.959      194874.349
     1958164.009      194633.327
#Sta/Elev= 30
       0 1863.84    29.8 1846.51    49.7 1840.16    79.6 1823.61    89.5 1819.72
   119.4 1812.71   159.2 1810.65     189 1803.33   208.9 1793.54   228.8 1780.09
   238.8  1778.3   288.5 1740.31   308.4 1727.97   328.3    1720   360.2 1717.12
   368.1 1716.98   375.2 1717.48   397.9 1721.28   447.7 1733.64   507.4 1767.86
   537.2 1789.44   576.3 1798.88   605.4 1812.49   644.2 1836.97   653.9 1837.29
   692.7 1859.61   731.6 1885.67   741.3 1886.51     751 1891.77   789.8 1918.66
#Mann= 3 , 0 , 0
       0      .1       0   360.2    .045       0   375.2      .1       0
Bank Sta=360.2,375.2
XS Rating Curve= 0 ,0
Exp/Cntr=0.3,0.1

Type RM Length L Ch R = 1 ,6140.3  ,566.1,535.5,505
XS GIS Cut Line= 3
     1958302.017      195546.546     1958544.484      195222.798
     1958711.647      194818.003
#Sta/Elev= 30
       0 1774.08    39.5 1762.98    59.2 1756.24    78.9 1747.63   108.5 1741.06
   118.4 1736.82   138.1 1734.05   226.9 1715.04   326.5 1703.12   345.3  1701.5
   355.2  1702.8   434.3 1716.06   474.2 1725.95   484.1 1734.24     514 1764.44
   543.8  1789.7   563.7 1809.54   573.7 1816.38   583.6 1818.82   603.6  1839.4
   613.5 1848.31   633.4 1861.41   663.3 1876.28   683.2 1881.27     713 1895.53
   762.8 1914.36   772.8 1915.48   792.7 1921.92   812.6 1925.86   842.4 1937.52
#Mann= 3 , 0 , 0
       0      .1       0   326.5    .045       0   355.2      .1       0
Bank Sta=326.5,355.2
XS Rating Curve= 0 ,0
Exp/Cntr=0.3,0.1

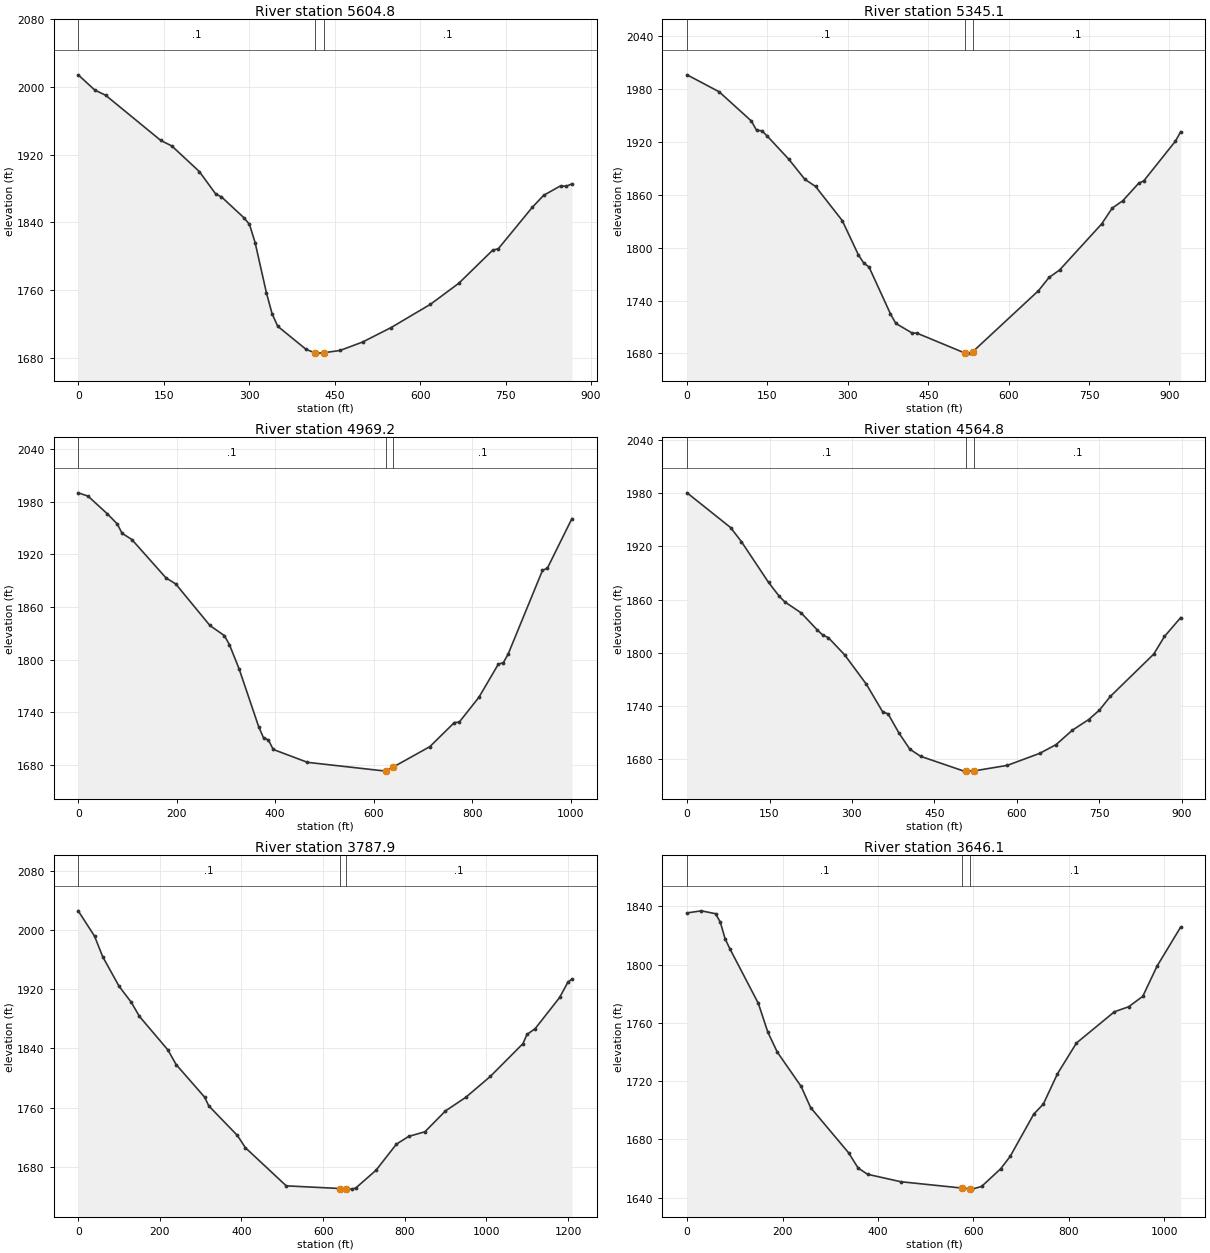
Type RM Length L Ch R = 1 ,5604.8  ,261.3,259.6,257.9
XS GIS Cut Line= 3
     1959183.713      195660.684     1959064.437      195428.759
     1958677.896      194962.701
#Sta/Elev= 30
       0 2014.44      29 1996.45    48.3 1990.22   144.9 1936.89   164.2 1930.42
   212.5 1900.18   241.5 1873.44   251.1  1870.4   290.6 1845.69   300.5 1837.77
   310.4 1816.24   330.3  1756.8   340.2  1732.2   350.1 1717.36   399.8  1690.1
   415.5  1685.9   419.6 1685.61   430.5 1686.04   459.3 1688.72     499 1698.72
   548.7 1715.68   618.1 1743.32   667.8 1768.12   727.3 1807.24   737.2 1808.95
   796.8 1857.87   816.7 1872.06   846.4 1883.24   856.4 1882.73   866.3 1885.63
#Mann= 3 , 0 , 0
       0      .1       0   415.5    .045       0   430.5      .1       0
Bank Sta=415.5,430.5
XS Rating Curve= 0 ,0
Exp/Cntr=0.3,0.1

Type RM Length L Ch R = 1 ,5345.1  ,359.3,375.9,392.4
XS GIS Cut Line= 3
     1959277.376      195574.327     1959161.625      195150.449
     1958832.231      194798.978
#Sta/Elev= 30
       0 1996.36    59.9 1977.08   119.8 1944.02   129.8 1933.25   139.8 1932.86
   149.8 1926.66   189.7 1900.57   219.7 1877.74   239.7 1869.61   289.6 1830.81
   319.6 1791.98   329.6 1782.67   339.5 1778.11   379.5 1724.91   389.5 1714.06
   419.4 1703.32   429.4 1702.88   518.4  1680.4   527.9 1680.32   533.4 1682.13
   655.7 1751.25   675.3 1766.22     695 1774.69   773.6 1827.07   793.3 1845.05
     813 1853.38   842.4 1873.11   852.3 1876.08   911.3 1921.12   921.1 1931.84
#Mann= 3 , 0 , 0
       0      .1       0   518.4    .045       0   533.4      .1       0
Bank Sta=518.4,533.4
XS Rating Curve= 0 ,0
Exp/Cntr=0.3,0.1

Type RM Length L Ch R = 1 ,4969.2  ,377.1,404.5,431.8
XS GIS Cut Line= 3
     1959369.547      195539.656     1959431.099      195128.361
     1959417.991      194541.776
#Sta/Elev= 30
       0 1990.25    19.8 1986.54    59.4 1966.18    79.2 1954.78    89.1 1944.09
   108.9 1937.01   178.2 1893.26     198 1886.35   267.4 1838.97     297  1827.3
     307  1817.2   326.8 1789.42   366.4  1723.7   376.3 1710.83   386.2 1708.36
   396.1 1697.57   465.6 1682.86   624.7 1672.83   624.9 1672.87   639.9 1677.54
   714.2 1700.79   763.9 1728.22   773.9 1728.78   813.7 1756.98   853.4 1794.99
   863.4  1796.5   873.3 1806.52   942.9  1901.8   952.9 1904.37  1002.6  1960.8
#Mann= 3 , 0 , 0
       0      .1       0   624.9    .045       0   639.9      .1       0
Bank Sta=624.9,639.9
XS Rating Curve= 0 ,0
Exp/Cntr=0.3,0.1

Type RM Length L Ch R = 1 ,4564.8  ,776.2,776.7,777.3
XS GIS Cut Line= 3
     1959440.861      195585.536     1959607.803      195194.626
     1960038.864      194999.287
#Sta/Elev= 30
       0 1980.36    79.1 1941.28    98.8 1925.43   148.3  1879.4     168 1863.61
   177.9 1857.46   207.6 1845.09   237.2 1825.74   247.1 1820.01     257 1817.24
   286.7 1797.84   326.2 1764.77   355.9 1733.63   365.8 1731.31   385.5 1709.79
   405.3 1691.56   425.1 1683.47   503.9  1666.8   507.6 1666.86   522.6  1667.1
   582.8  1673.3     642 1686.91   671.6 1696.74   701.1 1712.92   730.7 1724.87
   750.4 1735.56   770.2 1750.98     849 1798.53   868.7 1818.52   898.3 1839.83
#Mann= 3 , 0 , 0
       0      .1       0   507.6    .045       0   522.6      .1       0
Bank Sta=507.6,522.6
XS Rating Curve= 0 ,0
Exp/Cntr=0.3,0.1

Type RM Length L Ch R = 1 ,3787.9  ,142.6,141.8,141
XS GIS Cut Line= 3
      1959466.44       196056.06     1960162.214      195751.245
     1960371.939      195353.247
#Sta/Elev= 30
       0 2026.06      40 1991.77      60 1963.98     100 1924.12   129.9 1902.41
   149.9 1883.34   219.9 1837.77   239.9  1818.1   309.8 1773.96   319.8 1762.26
   389.8 1722.29   409.8 1705.54   509.7 1654.05   641.5 1650.45   656.5 1649.99
   669.7 1649.61   679.6 1650.94   729.6 1675.15   779.6 1710.46   809.6 1720.91
   849.6 1727.24   899.6 1755.32   949.6 1773.82  1009.5 1801.97  1089.5 1846.34
  1099.5 1858.82  1119.5 1866.66  1179.5 1908.86  1199.5 1929.31  1209.5 1933.82
#Mann= 3 , 0 , 0
       0      .1       0   641.5    .045       0   656.5      .1       0
Bank Sta=641.5,656.5
XS Rating Curve= 0 ,0
Exp/Cntr=0.3,0.1

Type RM Length L Ch R = 1 ,3646.1  ,372.5,342.9,313.2
XS GIS Cut Line= 3
     1959609.782      196173.357     1960199.533      195884.003
     1960362.985      195543.847
#Sta/Elev= 30
       0 1835.52    29.9 1836.95    59.7 1834.97    69.7 1829.12    79.6 1817.81
    89.6 1810.94   149.3 1773.42   169.2 1753.65   189.1 1739.91   238.9 1716.43
   258.8 1701.88   338.4 1670.84   358.3 1660.39   378.2 1656.06   447.9 1650.95
   576.9 1646.57   591.9 1646.04   597.2 1645.87   617.1 1647.71   656.9  1659.8
   676.8 1668.29   726.4  1697.4   746.3 1704.21   776.1 1725.11   815.8 1746.18
   895.3 1767.65   925.1 1771.07   954.8 1778.25   984.6 1798.93  1034.3 1825.87
#Mann= 3 , 0 , 0
       0      .1       0   576.9    .045       0   591.9      .1       0
Bank Sta=576.9,591.9
XS Rating Curve= 0 ,0
Exp/Cntr=0.3,0.1

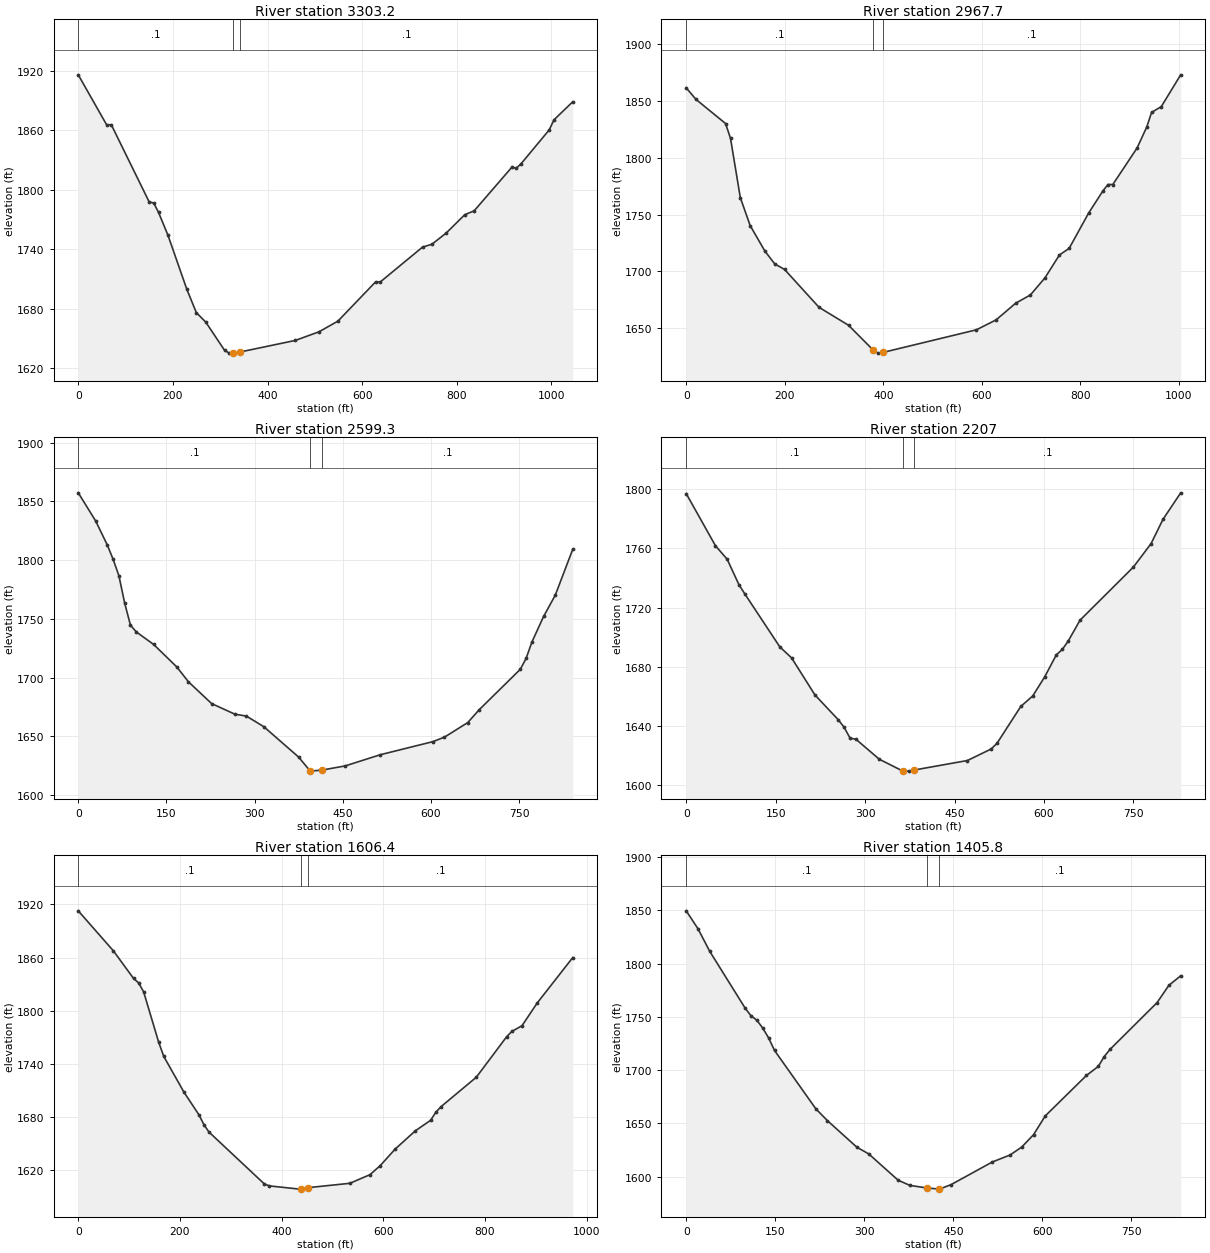
Type RM Length L Ch R = 1 ,3303.2  ,346.8,335.6,324.4
XS GIS Cut Line= 3
     1960431.688      196438.183     1960330.083      195868.311
     1960438.947      195414.844
#Sta/Elev= 30
       0 1916.04    59.9 1865.66    69.9 1865.61   149.7 1787.94   159.7 1786.54
   169.7 1777.17   189.6 1754.14   229.6 1699.42   249.5  1676.1   269.5 1666.47
   309.4 1637.89   319.4 1635.16   326.7 1635.19   341.7 1636.27   459.1 1648.01
     509 1656.72   548.9 1667.47   628.5 1707.09   638.4 1706.99   727.7 1742.17
   747.5 1745.05   777.3 1756.17     817 1774.87   836.8 1778.76   916.2 1822.62
   926.1 1821.87   936.1 1826.35   995.6 1860.55  1005.5  1870.6  1045.2 1888.84
#Mann= 3 , 0 , 0
       0      .1       0   326.7    .045       0   341.7      .1       0
Bank Sta=326.7,341.7
XS Rating Curve= 0 ,0
Exp/Cntr=0.3,0.1

Type RM Length L Ch R = 1 ,2967.7  ,373.5,368.3,367.3
XS GIS Cut Line= 3
     1960903.102      196244.865     1960480.282      195713.695
     1960527.407      195392.333
#Sta/Elev= 30
       0 1861.46      20 1851.26    79.9 1830.06    89.9 1817.02   109.8  1764.9
   129.8 1740.28   159.7 1717.81   179.7 1706.55   199.7 1701.64   269.6 1668.34
   329.5 1652.54   379.4 1630.77   389.4 1628.03   399.4 1628.65     589 1648.55
     629 1657.29   668.9 1672.01   698.6 1679.22   728.1 1694.23   757.6 1714.43
   777.3 1720.22   816.7 1751.21   846.2 1771.03   856.1 1776.43   865.9 1776.42
   915.1  1808.5   934.8 1827.01   944.6  1839.9   964.3 1844.97  1003.7 1872.95
#Mann= 3 , 0 , 0
       0      .1       0   379.4    .045       0   399.4      .1       0
Bank Sta=379.4,399.4
XS Rating Curve= 0 ,0
Exp/Cntr=0.3,0.1

Type RM Length L Ch R = 1 ,2599.3  ,385.3,392.3,395.1
XS GIS Cut Line= 3
     1961229.321      195877.308     1960891.297      195654.828
     1960604.043      195325.674
#Sta/Elev= 30
       0 1857.26    29.6 1833.32    49.4 1812.88    59.2 1800.84    69.1 1786.81
      79 1763.38    88.8 1744.66    98.7  1738.9   128.3 1728.19   167.8    1709
   187.5 1696.41     227 1677.86   266.5 1668.86   286.2 1667.22   315.8 1658.19
   375.1 1632.31   394.8 1620.38   414.6 1621.26   454.3 1624.82   513.9 1634.32
   603.2 1645.44   623.1 1649.27   662.8 1661.69   682.7 1672.83   752.2 1707.02
   762.1 1716.26     772 1730.22   791.9    1752   811.8 1770.16   841.5 1809.17
#Mann= 3 , 0 , 0
       0      .1       0   394.8    .045       0   414.6      .1       0
Bank Sta=394.8,414.6
XS Rating Curve= 0 ,0
Exp/Cntr=0.3,0.1

Type RM Length L Ch R = 1 ,2207    ,604.4,600.6,596.7
XS GIS Cut Line= 3
     1961372.399       195669.63     1961120.278      195331.149
     1960881.794       195000.99
#Sta/Elev= 30
       0 1797.01    49.1 1761.74    68.7 1752.69    88.3 1735.56    98.2 1729.29
     157 1693.44   176.7 1686.02   215.9 1660.97   255.2 1644.13     265 1639.02
   274.8 1631.77   284.6 1631.06   323.9 1617.51   363.2 1609.57     373  1609.5
   382.8 1610.28   471.7 1616.68   511.5 1624.48   521.4 1628.39   561.1  1653.2
     581 1660.22   600.9 1672.95   620.7 1688.06   630.7  1691.7   640.6 1697.33
   660.5  1711.5   749.9 1747.35   779.7 1763.27   799.5 1779.55   829.3 1797.54
#Mann= 3 , 0 , 0
       0      .1       0   363.2    .045       0   382.8      .1       0
Bank Sta=363.2,382.8
XS Rating Curve= 0 ,0
Exp/Cntr=0.3,0.1

Type RM Length L Ch R = 1 ,1606.4  ,200.4,200.6,199.8
XS GIS Cut Line= 3
     1961828.635      195255.594      1961390.31      194812.502
     1961087.703      194638.007
#Sta/Elev= 30
       0 1912.82    69.2 1867.56   108.8 1836.45   118.7 1831.49   128.6 1821.34
   158.3 1764.24   168.2 1748.44   207.8 1708.18   237.4 1682.51   247.3 1671.24
   257.2 1663.01     366 1604.49   375.9 1602.28   435.3 1598.63   437.8  1598.8
   452.8 1600.35   534.2  1605.2   573.8 1614.96   593.6 1624.94   623.3 1643.84
   663.2 1664.55   693.1 1676.37   703.1 1685.25   713.1 1691.53     783    1725
   842.8 1770.84   852.8 1776.66   872.8 1783.11   902.7 1808.76   972.6 1860.04
#Mann= 3 , 0 , 0
       0      .1       0   437.8    .045       0   452.8      .1       0
Bank Sta=437.8,452.8
XS Rating Curve= 0 ,0
Exp/Cntr=0.3,0.1

Type RM Length L Ch R = 1 ,1405.8  ,578.7,596.4,615
XS GIS Cut Line= 3
     1961914.154      195065.481     1961614.929      194761.625
     1961302.517      194501.554
#Sta/Elev= 30
       0  1849.6    19.8 1832.79    39.7 1811.49    99.2  1758.3   109.1 1751.07
     119 1746.89   128.9 1739.52   138.8  1730.3   148.8 1718.48   218.2 1663.84
     238 1652.54   287.6 1627.61   307.4 1621.42     357 1596.69   376.9 1591.81
   405.2 1589.45   426.5 1588.32   446.3 1592.57   515.7 1613.82   545.4 1620.31
   565.3 1627.86   585.1 1639.43   604.9 1657.08   674.3 1695.08   694.2 1703.51
   704.1 1712.73     714 1719.55   793.3 1763.47   813.1 1779.68     833 1788.59
#Mann= 3 , 0 , 0
       0      .1       0   405.2    .045       0   426.5      .1       0
Bank Sta=405.2,426.5
XS Rating Curve= 0 ,0
Exp/Cntr=0.3,0.1