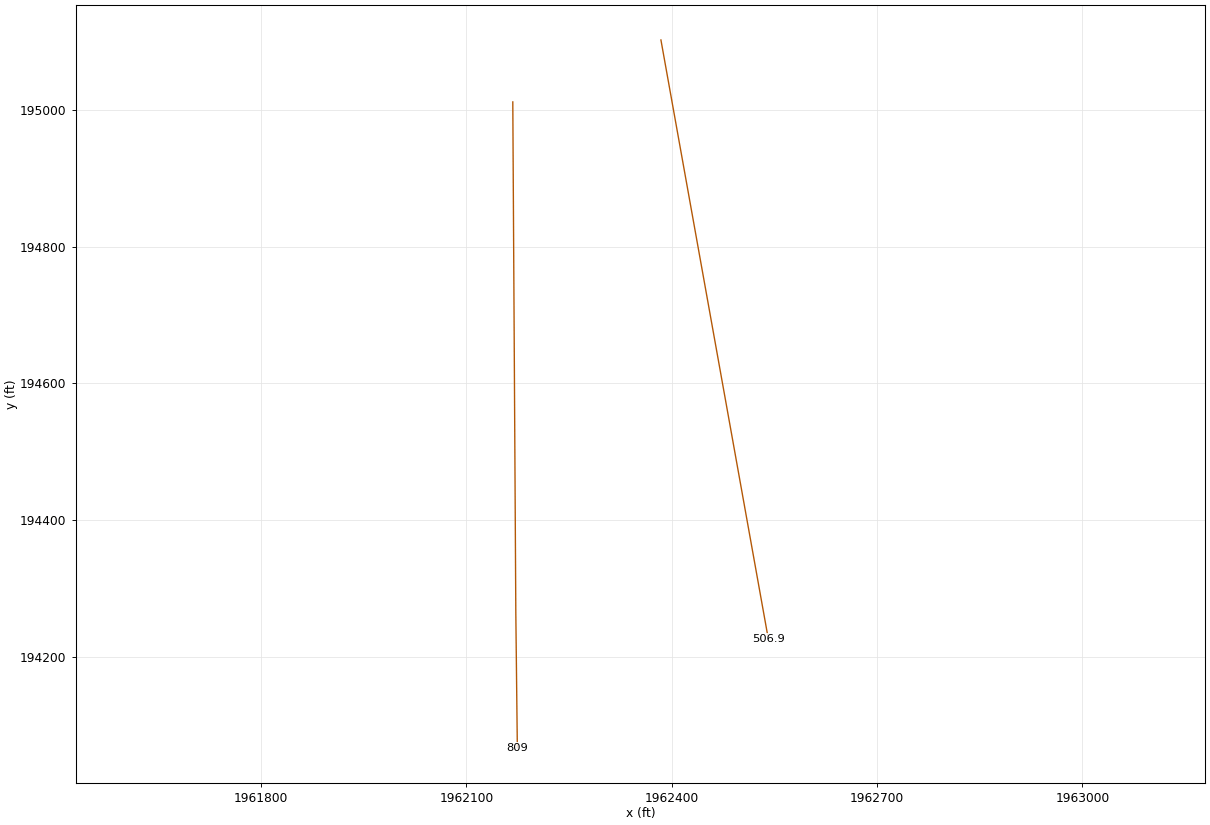
HEC-RAS study MntnCrk.prj: MntnCrk

--- MntnCrk.g01 (geometry) --- (continued)

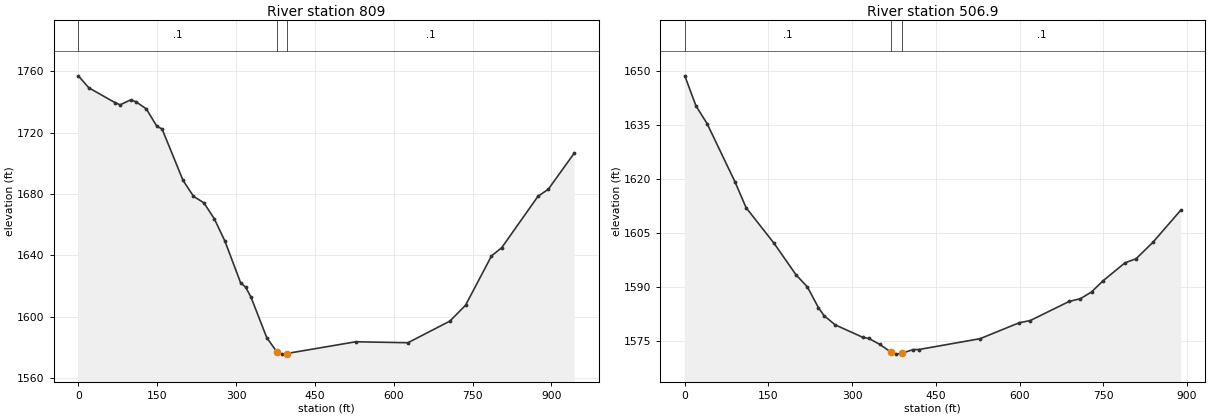
Type RM Length L Ch R = 1 ,809     ,298.1,301.9,305.7
XS GIS Cut Line= 3
     1962167.809      195011.295     1962172.227      194264.718
     1962174.436      194068.135
#Sta/Elev= 30
       0 1756.97    19.9 1749.19    69.7 1739.52    79.6 1738.08    99.6 1741.29
   109.5 1740.13   129.4  1735.4   149.3 1724.11   159.3 1722.34   199.1 1688.89
     219 1678.49   238.9  1674.2   258.8 1663.73   278.7 1649.39   308.6  1622.2
   318.5 1619.15   328.5 1612.69   358.4  1586.4   378.3 1576.77   388.2 1575.62
   396.3 1576.01   527.6 1583.67   627.1 1583.06   706.8 1597.15   736.6  1607.5
   785.9 1639.56   805.6 1645.08   874.4 1678.47     894 1683.05   943.2 1706.53
#Mann= 3 , 0 , 0
       0      .1       0   378.3    .045       0   396.3      .1       0
Bank Sta=378.3,396.3
XS Rating Curve= 0 ,0
Exp/Cntr=0.3,0.1

Type RM Length L Ch R = 1 ,506.9   ,523.2,507.2,491.1
XS GIS Cut Line= 2
     1962384.202      195101.814     1962541.027      194227.127
#Sta/Elev= 30
       0 1648.69      20 1640.35    39.9 1635.42    89.9 1619.25   109.8 1612.06
   159.8 1602.18   199.7 1593.31   219.7 1590.03   239.6 1584.23   249.6 1582.04
   269.6 1579.47   319.5 1575.98   329.5 1575.72   349.5 1574.04   369.4  1571.9
   379.4 1571.34   389.4 1571.62   409.4  1572.6   419.4 1572.62   529.2 1575.63
   599.1 1580.05     619 1580.67   688.9 1585.99   708.9 1586.74   728.9 1588.62
   748.8 1591.62   788.8 1596.71   808.8 1597.86   838.7 1602.38   888.6 1611.31
#Mann= 3 , 0 , 0
       0      .1       0   369.4    .045       0   389.4      .1       0
Bank Sta=369.4,389.4
XS Rating Curve= 0 ,0
Exp/Cntr=0.3,0.1

Chan Stop Cuts=-1
Use User Specified Reach Order=0
Composite Channel Slope=5